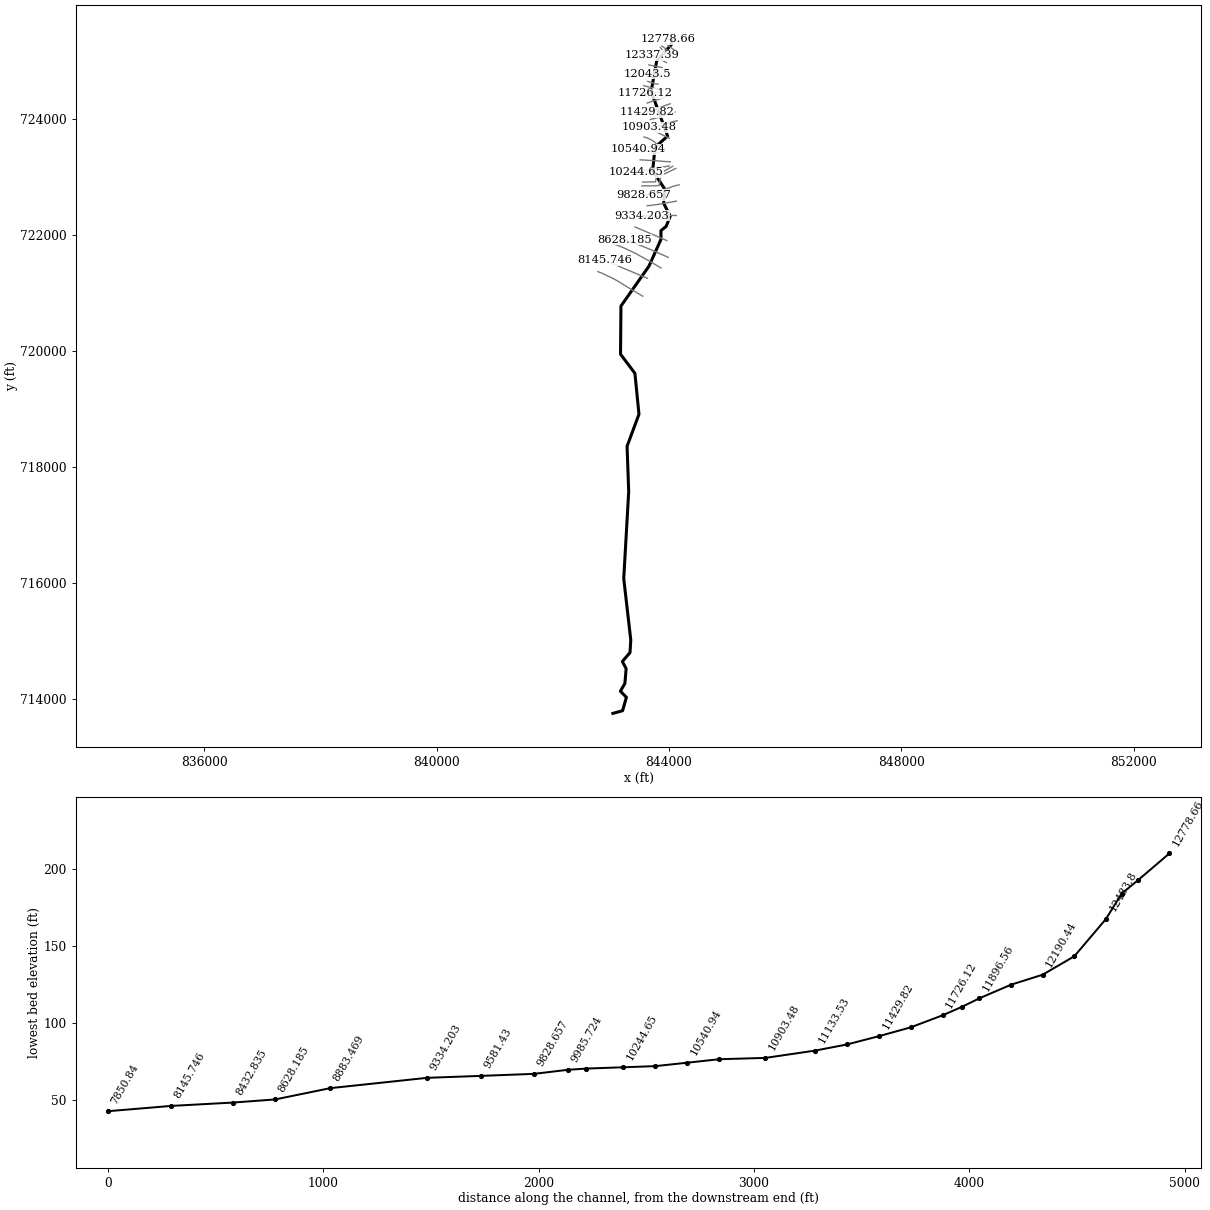
--- 7775_ras.prj (project) ---

Proj Title=7775
Current Plan=p01
Default Exp/Contr=0.3,0.1
English Units
Geom File=g01
Flow File=f01
Plan File=p01
Y Axis Title=Elevation
X Axis Title(PF)=Main Channel Distance
X Axis Title(XS)=Station
BEGIN DESCRIPTION:
RFD model 7775 exported to HEC-RAS
END DESCRIPTION:

--- 7775_ras.p01 (plan) ---

Plan Title=Plan 01
Program Version=4.10
Short Identifier=Plan 01
Geom File=g01
Flow File=f01
Subcritical Flow
Calc Critical at every XS
Secant Critical Depth

--- 7775_ras.f01 (steady flow) ---

Flow Title=Flow 01
Program Version=5.01
Number of Profiles= 6
Profile Names=10yr,25yr,50yr,100yr,100plus,500yr
River Rch & RM=7775,56,12778.66
  273.01  433.57  582.68  717.18 1047.09 1685.72
River Rch & RM=7775,56,12631.72
  404.75  644.38  867.71 1069.28 1561.15 2380.71
River Rch & RM=7775,56,12557.38
  549.13   877.3 1184.36 1462.18 2134.78 3126.49
River Rch & RM=7775,56,12337.39
  555.19  887.35 1198.27 1479.71 2160.37 3160.33
River Rch & RM=7775,56,12190.44
  556.61  889.71 1201.54 1483.85 2166.42 3168.37
River Rch & RM=7775,56, 12043.5
  557.74  891.59 1204.16 1487.16 2171.25 3174.79
River Rch & RM=7775,56,11896.56
  562.31  899.19 1214.68 1500.44 2190.64 3200.44
River Rch & RM=7775,56,11815.03
  566.02  905.35 1223.23 1511.21 2206.37 3221.21
River Rch & RM=7775,56,11726.12
  724.48 1165.96    1582 1961.29 2863.48 4059.87
River Rch & RM=7775,56,11577.97
  726.62 1169.52 1586.95 1967.54 2872.61 4071.52
River Rch & RM=7775,56,11429.82
  738.02 1188.43 1613.13 2000.53 2920.78 4132.49
River Rch & RM=7775,56,11281.68
  739.35 1190.64  1616.2 2004.42 2926.46 4139.72
River Rch & RM=7775,56,11133.53
  741.77 1194.66 1621.77 2011.45 2936.72 4152.73
River Rch & RM=7775,56,10903.48
  752.53 1212.53 1646.53 2042.68 2982.31 4210.36
River Rch & RM=7775,56,10689.09
   764.1 1231.98 1673.67 2077.14 3032.62 4274.82
River Rch & RM=7775,56,10540.94
  765.11 1233.68 1676.05 2080.17 3037.05 4280.54
River Rch & RM=7775,56,10392.79
   862.9 1394.55 1897.64 2358.19 3442.95 4780.38
River Rch & RM=7775,56,10244.65
  865.35 1398.69 1903.44 2365.58 3453.75 4794.04
River Rch & RM=7775,56,10070.45
   867.8 1402.83 1909.24 2372.97 3464.53 4807.69
River Rch & RM=7775,56,9985.724
  991.97 1609.27 2195.55 2734.35 3992.16  5453.9
River Rch & RM=7775,56, 9581.43
  996.27 1616.52  2205.7 2747.28 4011.02 5477.25
River Rch & RM=7775,56,9334.203
  1013.5 1645.56 2246.33 2798.94 4086.46 5570.23
River Rch & RM=7775,56,8883.469
 1135.67 1851.87 2535.32  3166.9 4623.68  6227.3
River Rch & RM=7775,56,8628.185
 1141.09 1861.08 2548.28 3183.46 4647.85 6256.84
River Rch & RM=7775,56,8432.835
 1143.77 1865.65 2554.72  3191.7 4659.88 6271.59
River Rch & RM=7775,56,8145.746
 1151.14  1878.2 2572.41 3214.34 4692.93 6312.08
River Rch & RM=7775,56, 7850.84
  1197.7 1957.15 2683.28 3355.84 4899.53 6562.61
River Rch & RM=7775,56,7610.734
    1268 2076.93 2852.06 3571.81 5214.84 6944.52
River Rch & RM=7775,56,7403.703
 1274.09 2087.32 2866.69 3590.55  5242.2 6977.54
River Rch & RM=7775,56,7228.443
  1275.8 2090.25 2870.84 3595.87 5249.97 6986.97
River Rch & RM=7775,56,6963.572
 1279.66 2096.85 2880.17 3607.84 5267.44 7008.15
River Rch & RM=7775,56,6614.704
 1283.29 2103.08 2888.97 3619.13 5283.94 7028.13
River Rch & RM=7775,56,6310.102
 1287.78 2110.76 2899.83 3633.08 5304.29 7052.79
River Rch & RM=7775,56, 6120.25
 1295.26 2123.56 2917.93 3656.29 5338.18 7093.81
River Rch & RM=7775,56,5877.082
  1312.3 2152.75 2959.18 3709.23 5415.48 7187.22
River Rch & RM=7775,56,5625.796
 1313.56 2154.92 2962.25 3713.18 5421.24  7194.2
River Rch & RM=7775,56,5415.712
 1315.04 2157.45 2965.83 3717.78 5427.96 7202.35
River Rch & RM=7775,56,5148.248
 1327.46 2178.78 2996.03 3756.58 5484.61 7270.88
River Rch & RM=7775,56,4828.934
 1851.32  3064.5 4238.68 5340.43 7797.03 9938.51
River Rch & RM=7775,56,4572.943
 1860.89 3080.94 4261.96 5370.35 7840.71  9988.7
River Rch & RM=7775,56, 4389.66
 1862.84 3084.28  4266.7 5376.45 7849.61 9998.93
River Rch & RM=7775,56,4102.996
 1864.78 3087.62 4271.43 5382.53  7858.510009.16
River Rch & RM=7775,56, 3978.74
 1867.49 3092.28 4278.05 5391.05 7870.9310023.47
River Rch & RM=7775,56,3705.264
 1868.46 3093.95 4280.41 5394.09 7875.3710028.58
River Rch & RM=7775,56,3476.929
  1915.9 3175.49 4396.01 5542.78 8092.4510277.71
River Rch & RM=7775,56,3248.594
 1919.76 3182.11 4405.41 5554.87 8110.1110297.94
River Rch & RM=7775,56,3020.259
 1922.45 3186.75 4411.98 5563.33 8122.46 10312.1
River Rch & RM=7775,56,2791.924
 1926.67 3194.01 4422.29  5576.6 8141.8310334.32
River Rch & RM=7775,56,2585.215
 1927.05 3194.67 4423.23  5577.8 8143.5910336.34
River Rch & RM=7775,56,2469.751
 1929.35 3198.63 4428.84 5585.04 8154.1610348.45
River Rch & RM=7775,56, 2358.18
 1930.31 3200.28 4431.19 5588.05 8158.56 10353.5
River Rch & RM=7775,56, 2069.63
 1936.25  3210.5 4445.69 5606.73 8185.8310384.76
River Rch & RM=7775,56,1609.712
 1973.16 3274.03 4535.84 5722.78 8355.2510578.58
River Rch & RM=7775,56,1149.794
 1977.34 3281.24 4546.08 5735.96  8374.510600.58
Boundary for River Rch & Prof#=7775,56,1
Up Type= 0
Dn Type= 2
Boundary for River Rch & Prof#=7775,56,2
Up Type= 0
Dn Type= 2
Boundary for River Rch & Prof#=7775,56,2
Up Type= 0
Dn Type= 2
Boundary for River Rch & Prof#=7775,56,2
Up Type= 0
Dn Type= 2
Boundary for River Rch & Prof#=7775,56,2
Up Type= 0
Dn Type= 2
Boundary for River Rch & Prof#=7775,56,2
Up Type= 0
Dn Type= 2

--- 7775_ras.g01 (geometry) ---

Geom Title=7775
Program Version=4.10

River Reach=7775,56
Reach XY= 30
844046.194591286  725372.5647488844040.356522129725272.861376179
843787.297929333724994.625790922843692.004884769724466.165120994
843975.710029543723699.921783594843758.481994223723505.144726719
843719.088218099723107.137343151843925.727614648722785.952885434
843907.977107009722540.470676409844019.782662557722320.331787538
843950.338218098722143.942898727843860.754884771722071.720676429
843860.754884771721920.331787622 843654.73945655721460.234266325
843171.865995886720772.415120919843164.966106285719943.644786747
843412.507372122719614.671829274843482.199887498718910.161290305
 843277.42155145718359.220676443843305.581917968717580.414251193
843220.049974621716081.696993505843341.310440341715023.977620917
843328.289607004714807.831787552843196.345162553714654.185954294
843261.449329221714530.922065367843239.747940328714274.845676507
843162.490995894714142.901231997843265.789607007714037.866509829
 843200.26306991713806.934264559843033.150718104713760.956787595

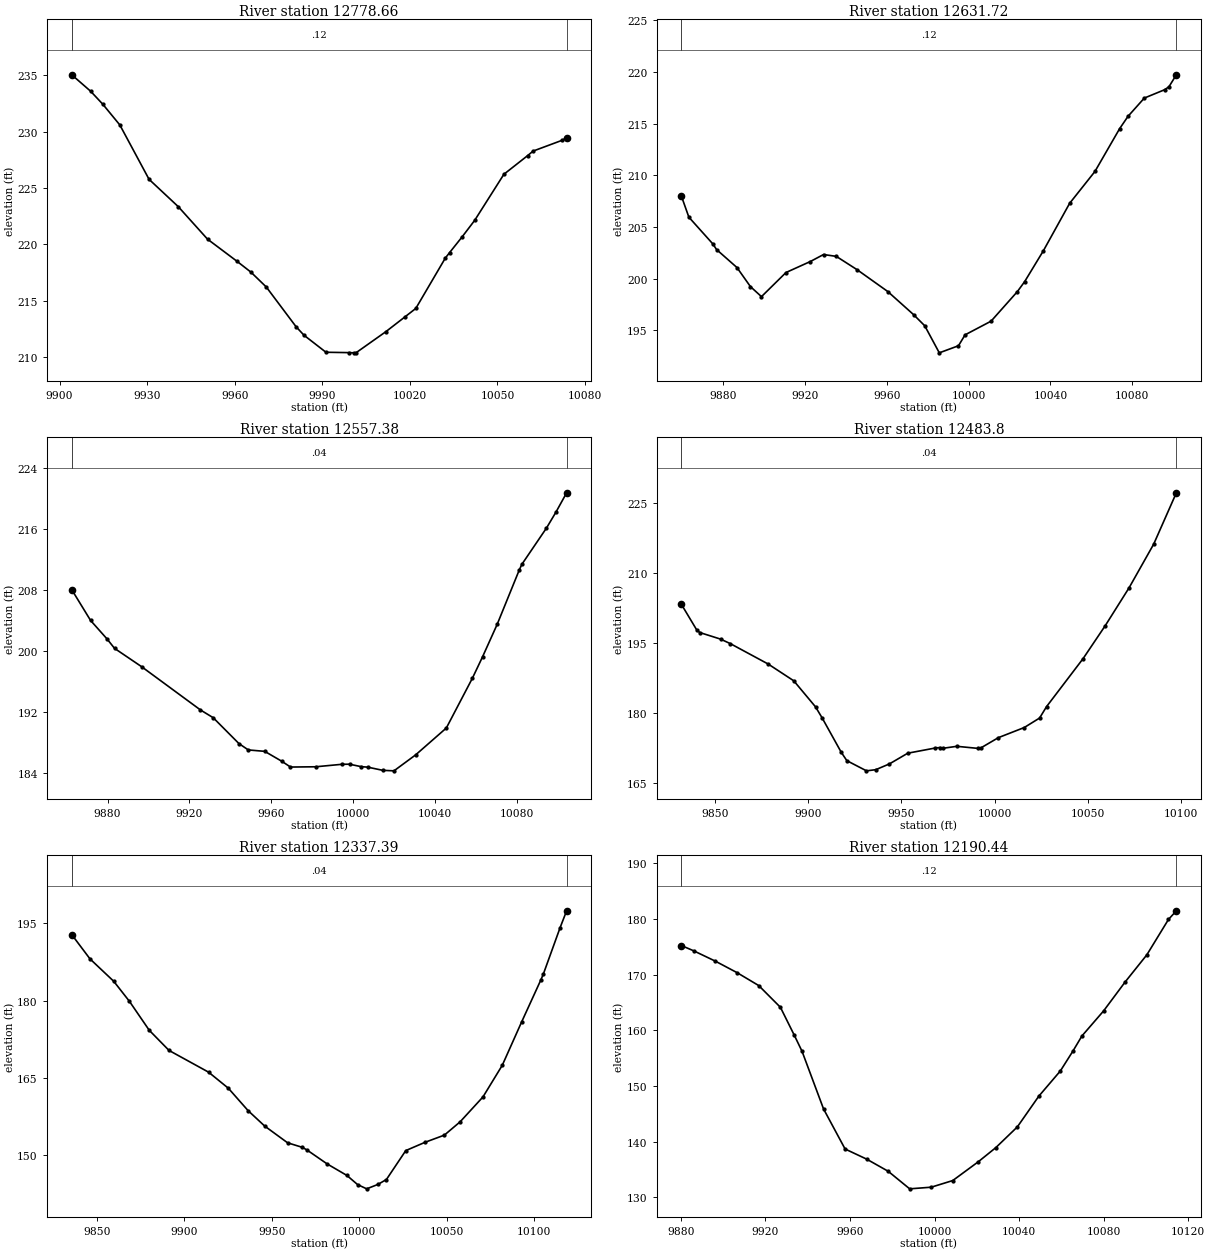
Type RM Length L Ch R = 1 ,12778.66,146.942800,146.942800,146.942800
XS GIS Cut Line= 6
844141.440467684725380.742591187844130.817539173 725381.50705835
844080.181907024725378.724132377844028.821691898725367.239287376
 844009.38335409725364.390371806843973.542696575725364.529002597
#Sta/Elev= 28
9904.181235.04449910.638233.58969914.831232.43059920.658230.59429930.673225.7702
9940.688223.34349950.703 220.4629960.718218.51569965.543217.54229970.837 216.217
9981.053212.68839983.751  211.949991.269210.4303    9999210.3983   10001210.3796
10001.53 210.37910011.82 212.26310018.18213.539210022.04214.316610032.15218.7825
10033.62219.271710037.83220.639310042.21222.129110052.22226.219110060.31227.8657
10062.23228.276510072.25229.241210073.71229.4743
#Mann= 3 , 0 , 0
9904.181    0.12       09904.181    0.12       010073.71    0.12       0
#XS Ineff= 2 , 0
       0                               0
Bank Sta=9904.181,10073.71
Exp/Cntr=0.3,0.1

Type RM Length L Ch R = 1 ,12631.72,74.339500,74.339500,74.339500
XS GIS Cut Line= 6
844128.130242813725157.260258075844113.309356652725165.917973384
844075.110223964 725191.05714388844012.824437618725238.566320582
843970.638137802725272.169322196843932.009469525  725298.1614968
#Sta/Elev= 30
 9859.77207.96339863.395205.93839875.114203.34989876.934202.80529886.881201.0677
9893.454199.22559898.852 198.2529910.824200.58549922.663201.64479929.161202.3252
9935.383202.1495 9945.64 200.8489960.545198.74629973.126196.51519978.599195.4341
9985.707192.81629995.078193.50249998.289194.5563   10011195.880410023.79198.7276
10027.38199.699610036.57202.701310049.36207.277710061.73210.363510073.78214.5014
10077.92215.704510085.84217.460510095.83218.273710097.89218.562210101.49219.7135
#Mann= 3 , 0 , 0
 9859.77    0.12       0 9859.77    0.12       010101.49    0.12       0
#XS Ineff= 2 , 0
       09944.265                       0
Bank Sta=9859.77,10101.49
Exp/Cntr=0.3,0.1

Type RM Length L Ch R = 1 ,12557.38,73.584400,73.584400,73.584400
XS GIS Cut Line= 6
 844072.95449021725107.032643933844058.133599916725115.690378895
844019.934459028725140.829602154843957.648664983725188.338869959
843915.462361192725221.941934382843876.833685125725247.934162739
#Sta/Elev= 29
9862.492 208.0759871.704204.03439879.656201.63459883.408200.37229896.591197.9758
9925.385192.29219931.594191.27729944.175187.88139948.737187.05169956.756186.8656
9965.217185.54629969.337184.80669981.696184.84279994.499185.16819998.175185.1808
10003.72184.865610007.11184.790910014.41184.376710019.89184.309510030.46186.4005
10045.46 189.92610058.21196.469210063.13199.251910070.27203.507410081.05210.6313
10082.32211.381610094.37 216.15110098.96218.220510104.22220.7791
#Mann= 3 , 0 , 0
9862.492    0.04       09862.492    0.04       010104.22    0.04       0
#XS Ineff= 2 , 0
       09945.436                       0
Bank Sta=9862.492,10104.22
Exp/Cntr=0.3,0.1

Type RM Length L Ch R = 1 , 12483.8,146.407300,146.407300,146.407300
XS GIS Cut Line= 6
844011.585614029725018.897423061843976.948386886725045.754396315
843937.908223871725084.982667672843913.849975446725118.547532094
843873.408120837725194.679076737843848.787642595725224.364984416
#Sta/Elev= 30
9832.106 203.259 9840.44197.71389842.066197.23539853.094195.84419858.385194.8672
9878.613190.51769892.351186.92819904.004181.36379907.559178.9945  9917.8171.6494
9920.802169.8579 9931.34167.68059936.311167.92579943.643 169.1649953.476171.4528
 9968.25172.56439970.641172.65899972.615172.51939979.804172.92429990.945172.4876
9992.691172.585410002.09174.781310015.95176.940710024.17178.968310027.91181.4143
10047.53191.692410059.37198.710410072.12206.790210085.35216.140910097.52227.1342
#Mann= 3 , 0 , 0
9832.106    0.04       09832.106    0.04       010097.52    0.04       0
#XS Ineff= 2 , 0
       09962.705                       0
Bank Sta=9832.106,10097.52
Exp/Cntr=0.3,0.1

Type RM Length L Ch R = 1 ,12337.39,146.942800,146.942800,146.942800
XS GIS Cut Line= 5
843954.232807287724963.861777574843809.603373931725039.596214092
843807.848600803725040.555782324843793.992832011725047.774563707
843701.638480867725090.600507444
#Sta/Elev= 30
9835.741192.79639846.163188.09059859.752183.7386 9868.74179.83949880.028174.2457
9891.316170.33939913.892166.1308 9925.18163.01849936.468158.67279945.979155.6725
9959.044 152.4339967.535151.54549970.332150.9904 9981.62 148.3439992.908146.1075
    9999144.340510004.21143.509510010.62144.364510015.49145.318710026.54150.9247
10037.56152.534210048.58153.922710057.57156.496810070.63161.326210081.65167.4544
10092.67175.8281 10103.7184.011410105.11 185.13410114.72194.169610118.42197.4123
#Mann= 3 , 0 , 0
9835.741    0.04       09835.741    0.04       010118.42    0.04       0
#XS Ineff= 2 , 0
       0                               0
Bank Sta=9835.741,10118.42
Exp/Cntr=0.3,0.1

Type RM Length L Ch R = 1 ,12190.44,146.942700,146.942700,146.942700
XS GIS Cut Line= 6
843880.618971018724876.700788823843877.653296752724877.498559599
843828.543159636724888.628906538843762.484030724  724901.3194848
843699.112206101724913.429726473843651.367594352724923.809688686
#Sta/Elev= 27
9880.306175.20869886.098 174.2699896.351172.40949906.605170.34859916.859168.0277
9927.112164.12539933.733159.06269937.341156.22239947.523145.86299957.706138.6747
9967.888136.86059978.071134.68049988.253131.52239998.436131.816810008.62  133.01
10020.61136.357610028.98  138.9210039.16 142.64110049.34148.172310059.52152.6963
10065.52156.298810069.73158.983410079.96163.474110090.19 168.69110100.43173.5535
10110.66 179.90910114.38 181.459
#Mann= 3 , 0 , 0
9880.306    0.12       09880.306    0.12       010114.38    0.12       0
#XS Ineff= 2 , 0
       0                               0
Bank Sta=9880.306,10114.38
Exp/Cntr=0.3,0.1

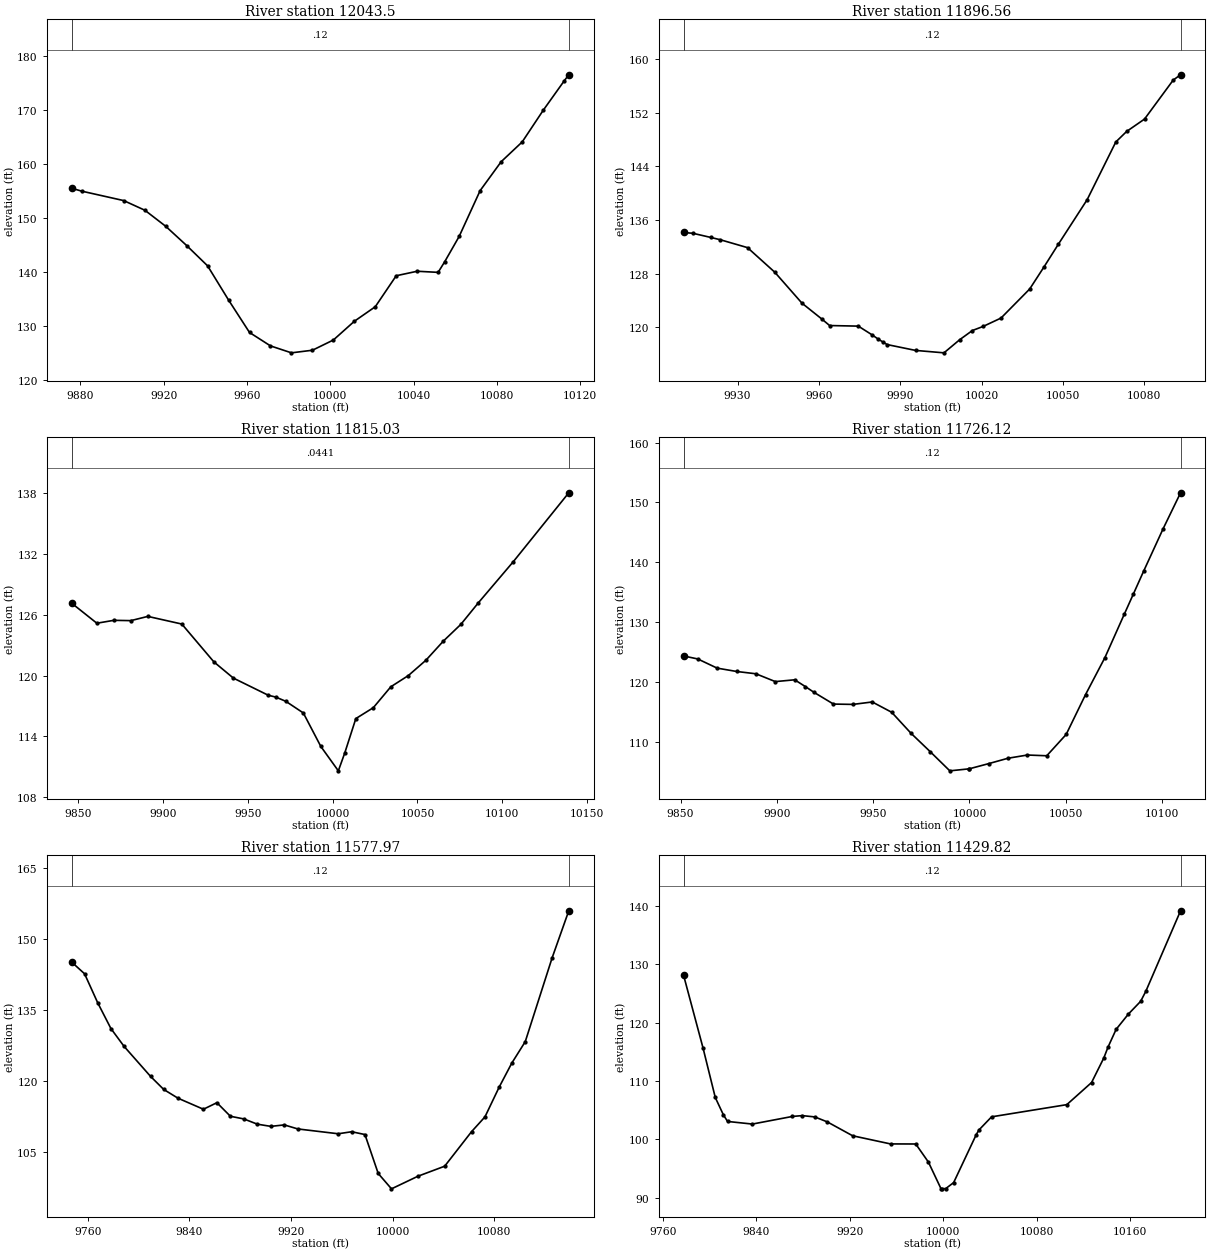
Type RM Length L Ch R = 1 , 12043.5,146.942800,146.942800,146.942800
XS GIS Cut Line= 5
843869.749773864 724740.96315831 843747.48499227724755.121973684
843745.494495758724755.316713554843691.871762373724761.060352717
843632.846776976724769.251678038
#Sta/Elev= 26
9875.918155.4914  9880.7154.96099900.833153.2158 9911.01151.42379920.967148.4665
9931.034   144.99941.101141.13369951.167134.80459961.234128.79589971.301 126.311
9981.368125.02629991.435125.5087 10001.5127.404910011.55130.867610021.61133.5632
10031.67139.301410041.73140.133210051.78139.926810054.93141.884210061.87146.5687
10071.96155.063910082.06160.415810092.15164.075510102.25169.938810112.35175.4002
10114.52176.5102
#Mann= 3 , 0 , 0
9875.918    0.12       09875.918    0.12       010114.52    0.12       0
#XS Ineff= 2 , 0
       0                               0
Bank Sta=9875.918,10114.52
Exp/Cntr=0.3,0.1

Type RM Length L Ch R = 1 ,11896.56,81.526100,81.526100,81.526100
XS GIS Cut Line= 6
843808.464500598724594.045214206843757.795013775724598.878706931
843738.162551655724605.715034535843736.322502646724606.498758782
843701.220513267 724617.59821671843632.441874003724641.539450214
#Sta/Elev= 29
9910.088134.13979913.568134.01549920.142133.39639923.614133.05679933.659131.8782
9943.704128.2124 9953.75123.58239960.987121.24249963.947120.24049974.536120.1526
9979.602118.85319981.776118.24499983.776117.73949985.163117.39889995.651116.5245
10006.14116.162710011.97118.134910016.63119.498710020.59120.108210027.18121.3578
10037.77125.701610043.11129.039510048.35132.395710058.94139.025910069.53 147.658
10073.53149.233810080.12151.077610090.71156.905710093.42157.6957
#Mann= 3 , 0 , 0
9910.088    0.12       09910.088    0.12       010093.42    0.12       0
#XS Ineff= 2 , 0
       0                               0
Bank Sta=9910.088,10093.42
Exp/Cntr=0.3,0.1

Type RM Length L Ch R = 1 ,11815.03,88.915700,88.915700,88.915700
XS GIS Cut Line= 3
843849.732102022 724511.15723609843766.111392846724516.040218452
843563.297929884724567.469306589
#Sta/Elev= 25
9846.225 127.1489860.982125.18039870.999125.46649881.016125.43669891.033125.8545
9911.067125.09929929.988121.35789941.451119.75929962.084118.0593 9966.44117.8834
9972.401117.46279982.717 116.3119993.034113.002210003.35110.592710007.12112.3475
10013.67115.756810023.98116.8345 10034.3118.899910044.62120.006810054.93121.5129
10065.25 123.41110075.57125.064310085.88127.193210106.52131.263610139.22 138.071
#Mann= 3 , 0 , 0
9846.225  0.0441       09846.225  0.0441       010139.22  0.0441       0
#XS Ineff= 2 , 0
       0                               0
Bank Sta=9846.225,10139.22
Exp/Cntr=0.3,0.1

Type RM Length L Ch R = 1 ,11726.12,148.147000,148.147000,148.147000
XS GIS Cut Line= 2
843842.295289724724462.416377261 843585.99168155724432.114145782
#Sta/Elev= 30
9851.554124.33749858.901123.8397 9868.97 122.306 9879.04121.74929889.109121.3609
9899.179120.05479909.249120.35559914.721119.23479919.318118.24949929.388116.2986
9939.458116.24319949.527116.65079959.597 114.9319969.667111.41389979.736108.3084
9989.806105.14089999.876105.47729999.892105.478610009.95106.342510020.01107.2447
10030.08107.783710040.15107.661110050.22111.219810060.29117.881710070.36124.0707
10080.43131.330710085.06134.6409 10090.5138.540610100.57145.592710109.64151.6108
#Mann= 3 , 0 , 0
9851.554    0.12       09851.554    0.12       010109.64    0.12       0
#XS Ineff= 2 , 0
       0                               0
Bank Sta=9851.554,10109.64
Exp/Cntr=0.3,0.1

Type RM Length L Ch R = 1 ,11577.97,148.147000,148.147000,148.147000
XS GIS Cut Line= 6
843994.725807694724387.129116509843991.059025054724386.368762777
843900.555351767724361.215415672843787.100848531724320.924061839
843723.931036812724302.042261885843622.601061885724267.213921097
#Sta/Elev= 30
9747.437145.14989757.471 142.707 9767.85136.55789778.229131.13249788.608 127.362
9809.366121.05049819.745118.28569830.983116.43739851.011114.10269861.623115.4841
9872.235  112.629882.847112.05389893.459110.94879904.071110.48599914.682110.7949
9925.294109.9429 9957.13108.92429967.707109.35189978.152108.75869988.597100.5349
9999.04297.29426 10019.999.9615810040.89102.072410062.04109.359810072.61112.4909
10083.87 118.81410093.76123.858310104.33128.379910125.48146.074710138.59156.0122
#Mann= 3 , 0 , 0
9747.437    0.12       09747.437    0.12       010138.59    0.12       0
#XS Ineff= 2 , 0
       0                               0
Bank Sta=9747.437,10138.59
Exp/Cntr=0.3,0.1

Type RM Length L Ch R = 1 ,11429.82,148.147000,148.147000,148.147000
XS GIS Cut Line= 6
844020.858561676724255.288395705843987.294495998724244.662637508
843931.766334761724224.646768727843757.521056367724152.697941575
 843704.94749015724132.588768636843622.228802804724106.691461464
#Sta/Elev= 30
9777.587128.11129794.222115.67839804.711107.19799811.675104.21959815.232103.0912
9836.492 102.6439870.777103.94859879.136104.09119889.949103.86839900.763 103.007
 9922.39100.63829954.83199.241899976.45999.229629987.27296.141599998.08691.57293
    999991.5478410002.2391.6039910008.9292.6176710028.28 100.83210030.58101.6289
10041.41103.882410105.86105.969310127.08109.7595 10137.6113.979610141.18115.8305
10148.11118.866310158.63121.487610169.14123.672310173.54125.380610203.32139.1781
#Mann= 3 , 0 , 0
9777.587    0.12       09777.587    0.12       010203.32    0.12       0
#XS Ineff= 2 , 0
       09964.578                       0
Bank Sta=9777.587,10203.32
Exp/Cntr=0.3,0.1

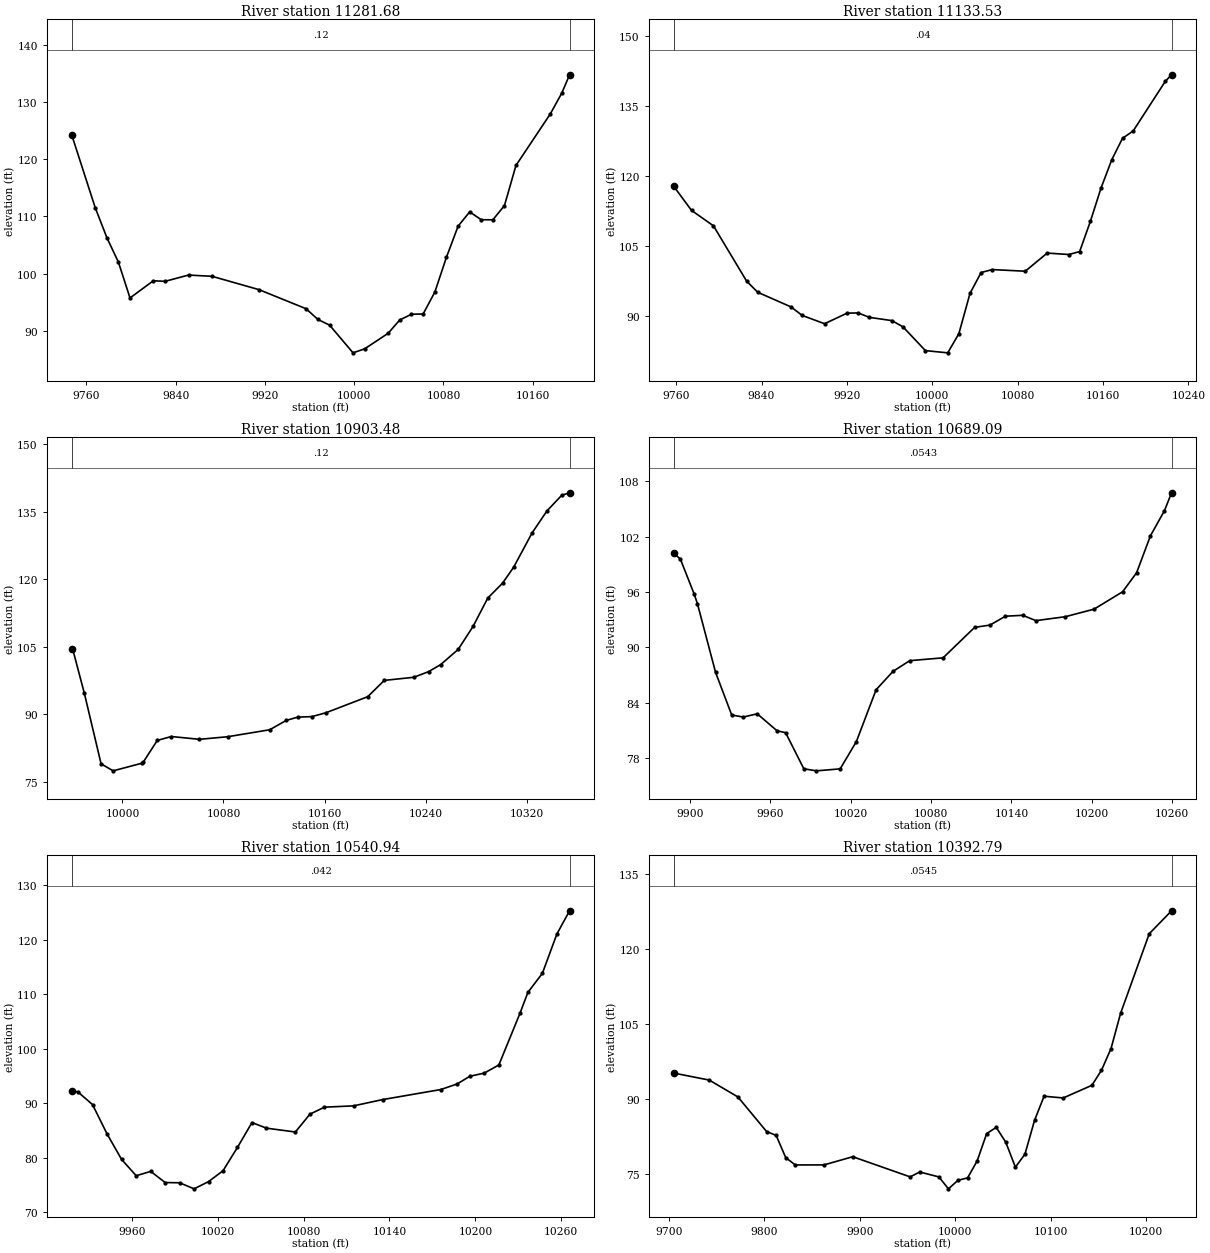
Type RM Length L Ch R = 1 ,11281.68,148.147000,148.147000,148.147000
XS GIS Cut Line= 6
844105.090825547724113.373532437844039.387606492724094.576948097
843881.356196907 724042.33429039 843787.66858649724013.041082815
843728.993791618723996.616477839843678.185560404723984.927683636
#Sta/Elev= 30
9747.031124.18469767.928111.55619778.329106.3229 9788.73102.02089799.13195.74976
9819.99198.756399830.52398.658179851.58899.756359872.65299.539359914.78197.20097
9956.91193.871529967.44392.003639977.97591.00183 9998.9986.1578210009.4786.86393
10030.4189.5707710040.8891.9083110051.3592.9009810061.8292.95279 10072.396.78599
10082.74102.895110093.13108.305910103.51110.8038 10113.9109.427510124.28109.4192
10134.67111.9038   10145118.926310175.79127.940710186.05131.571710193.04134.7742
#Mann= 3 , 0 , 0
9747.031    0.12       09747.031    0.12       010193.04    0.12       0
#XS Ineff= 2 , 0
       0                               0
Bank Sta=9747.031,10193.04
Exp/Cntr=0.3,0.1

Type RM Length L Ch R = 1 ,11133.53,230.050300,230.050300,230.050300
XS GIS Cut Line= 6
844141.127435212723963.875204645844049.422179288723940.383182198
 843851.09458783723878.227027017843806.573890642723867.600215194
843772.267872956723861.827701703843689.109196316723856.020193603
#Sta/Elev= 30
9757.805117.78379774.355112.66319794.925109.35939825.99597.525469836.35295.14093
9867.62391.998949878.11890.16934 9899.1188.403569920.10190.667769930.59790.70955
9941.09389.759689962.08489.07469 9972.5887.728029993.57282.6456810014.4982.16991
10024.9386.2704410035.3794.9024610045.8199.3635510056.25 99.995410087.1699.64131
 10107.7103.526610127.98103.219910138.12103.843710148.19110.315410158.22117.4822
10168.26123.5129 10178.3128.093910188.33129.6734 10218.4140.288710224.29141.6931
#Mann= 3 , 0 , 0
9757.805    0.04       09757.805    0.04       010224.29    0.04       0
#XS Ineff= 2 , 0
       09935.891                       0
Bank Sta=9757.805,10224.29
Exp/Cntr=0.3,0.1

Type RM Length L Ch R = 1 ,10903.48,214.390600,214.390600,214.390600
XS GIS Cut Line= 3
844005.799103095723660.689002848843814.775988837723753.690736151
843659.669616817723848.029868205
#Sta/Elev= 30
    9960104.54049960.888104.21039969.84894.696249983.13378.999299992.69377.44613
10015.5479.14612 10016.579.3609310027.6284.1992410038.7485.0622310060.9984.44033
10083.2385.01237 10116.686.5604110129.7688.6455910138.8489.3677610149.9789.48147
10161.0990.3329710194.2293.9073110207.3197.5203810230.72 98.212310242.4299.46776
10251.95101.022510265.83104.401910277.54109.482510289.24115.789510300.95119.1032
10309.68122.618410324.35130.270910336.06 135.12710347.76 138.602   10354139.1607
#Mann= 3 , 0 , 0
    9960    0.12       0    9960    0.12       0   10354    0.12       0
#XS Ineff= 2 , 0
       0                10050.36       0
Bank Sta=9960,10354
Exp/Cntr=0.3,0.1

Type RM Length L Ch R = 1 ,10689.09,148.147000,148.147000,148.147000
XS GIS Cut Line= 6
843878.783974419723485.591317044843838.276802121723517.899141283
843763.201155969723586.451222913843719.337578777 723619.12919232
843639.549887526723660.912456166843569.822775393723683.777676063
#Sta/Elev= 30
9887.859100.18919892.69999.582869902.94895.80657 9905.4994.720079918.98587.29087
9931.07382.642229939.67282.423179950.14782.772779964.89880.935719971.33580.72492
9984.93876.805239994.40176.5824910012.0876.7973710024.18 79.753710038.9385.39029
10051.5787.3826610064.0488.5432610088.9888.8524210112.5392.1584210124.0392.40914
10135.5393.3713310148.4293.4684510158.3292.8891710180.23 93.315610201.72 94.1347
10223.0696.02442 10233.598.0856710243.88102.109410254.27104.813910259.64106.7711
#Mann= 3 , 0 , 0
9887.859  0.0543       09887.859  0.0543       010259.64  0.0543       0
#XS Ineff= 2 , 0
       09948.656                       0
Bank Sta=9887.859,10259.64
Exp/Cntr=0.3,0.1

Type RM Length L Ch R = 1 ,10540.94,148.147000,148.147000,148.147000
XS GIS Cut Line= 6
843818.971369877723409.597840538843803.795921471723413.472002555
843766.843202841723420.323961961843668.234358274 723434.75868211
843510.348638786723462.677611332843476.205489885723467.938125676
#Sta/Elev= 30
9918.075 92.27899922.17492.141869932.49589.795679942.68384.394029952.854 79.7129
9963.024 76.73299973.18277.528749983.28475.480039993.38575.4364510003.4974.32582
 10013.675.6548510023.7177.6483710033.8181.9366910043.9286.4896910054.0385.46453
10074.2684.7557810084.4288.0322910094.5889.3169610114.8989.55404 10135.2 90.7059
10175.82 92.549910187.2293.5648610196.1394.9815410206.2895.5695710216.44 97.0643
10231.32 106.62210236.73110.385210246.85113.880410256.96121.082610265.86125.3601
#Mann= 3 , 0 , 0
9918.075   0.042       09918.075   0.042       010265.86   0.042       0
#XS Ineff= 2 , 0
       0 9931.84                       0
Bank Sta=9918.075,10265.86
Exp/Cntr=0.3,0.1

Type RM Length L Ch R = 1 ,10392.79,148.147000,148.147000,148.147000
XS GIS Cut Line= 6
844021.987040169723256.668184108843933.018133742723261.644962871
843744.318324418723275.584040517843728.725843181723276.586778776
843538.069330797723288.579246145843501.647799988723290.063859529
#Sta/Elev= 30
9705.05395.222179742.09893.832839772.14590.463129802.20183.548279812.22982.76925
9822.25678.339269832.28376.871479862.36576.878069892.447 78.5144 9952.6174.48826
9962.637 75.46139982.69274.483729992.71372.0979310002.7373.8080510012.7574.28447
10022.7777.6581510032.7983.1439510042.8184.3752710052.8381.4028110062.8576.42011
10072.8779.0193110082.8985.7600210092.9190.6006510112.95  90.25510143.0192.78214
10153.0395.7822810163.05100.127910173.07107.166510203.11123.073410226.49127.6549
#Mann= 3 , 0 , 0
9705.053  0.0545       09705.053  0.0545       010226.49  0.0545       0
#XS Ineff= 2 , 0
       09955.159        10035.92       0
Bank Sta=9705.053,10226.49
Exp/Cntr=0.3,0.1

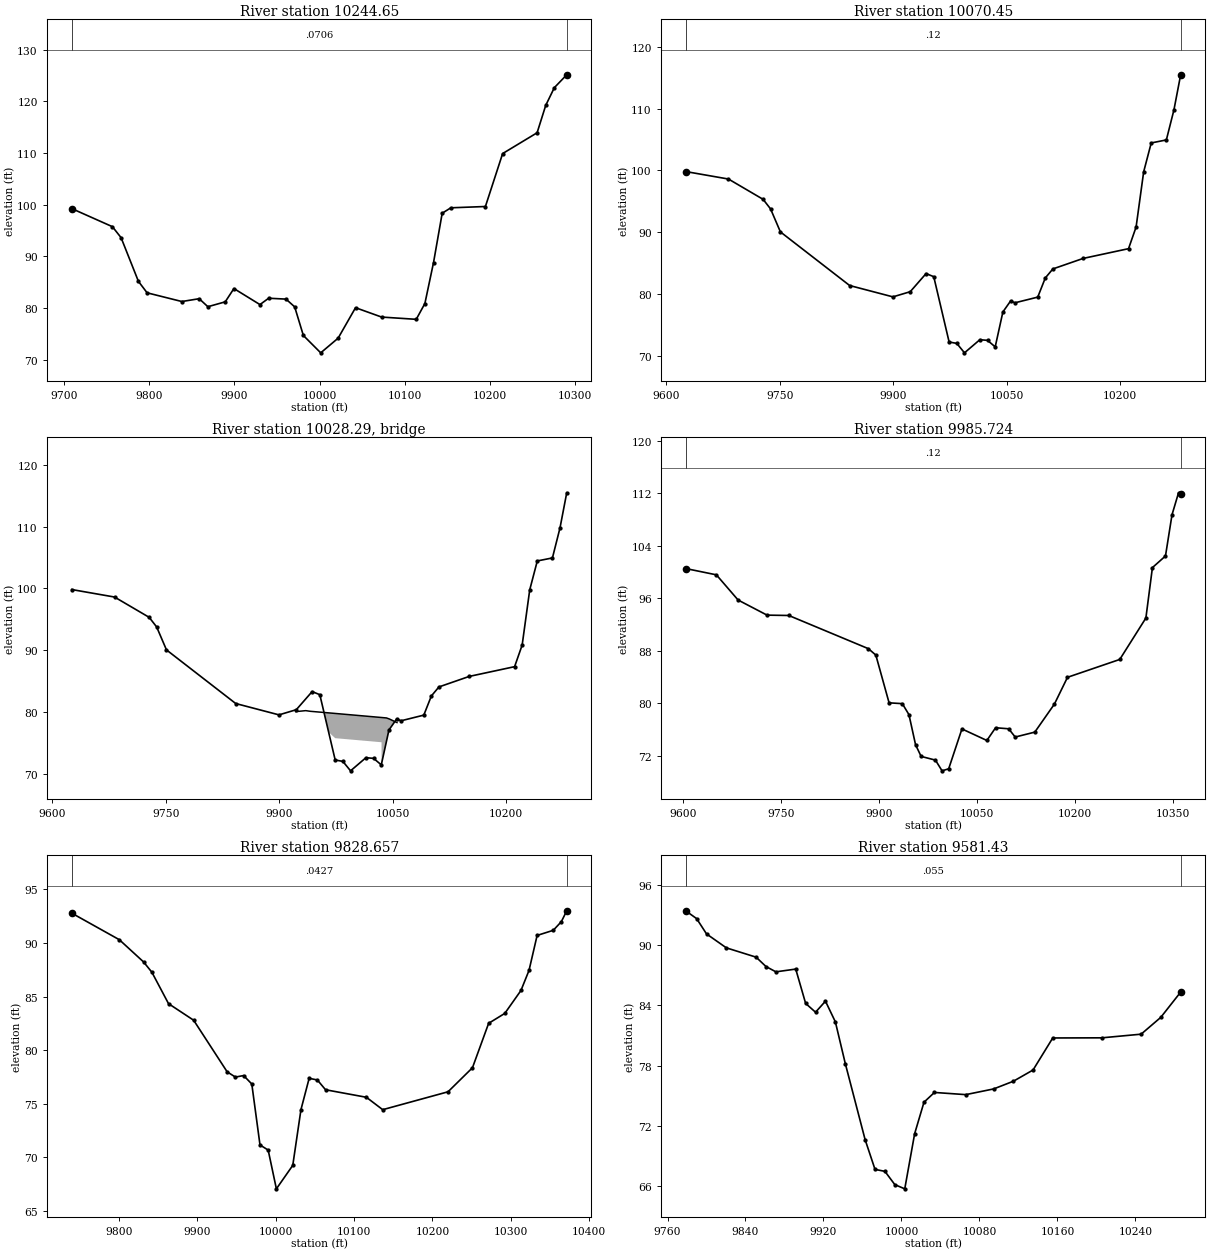
Type RM Length L Ch R = 1 ,10244.65,174.193500,174.193500,174.193500
XS GIS Cut Line= 6
844001.826273865 723186.02200543843709.150863758 723128.09983323
843707.216715392723127.590847223843644.966970816723114.638631286
843535.161335087723094.980508566843430.596814388723078.966035672
#Sta/Elev= 30
9708.98499.268689756.71895.768299766.91293.64734  9787.385.183939797.49482.96496
 9838.2781.282739858.65881.826539868.852 80.2776 9889.2481.221739899.43483.79188
9930.01580.687989940.20981.917699960.597  81.7499970.79180.245839980.98574.70869
10001.3771.3508210021.8174.1927910042.2480.0861910072.8878.2735210113.5277.83583
10123.6880.8966210133.8488.83007   1014498.3684610154.1699.4189910194.7599.66848
10214.98 109.91510255.45113.939810265.57119.234310275.68122.666410290.25125.1624
#Mann= 3 , 0 , 0
9708.984  0.0706       09708.984  0.0706       010290.25  0.0706       0
#XS Ineff= 2 , 0
       09947.888        10048.31       0
Bank Sta=9708.984,10290.25
Exp/Cntr=0.3,0.1

Type RM Length L Ch R = 1 ,10070.45,84.730700,84.730700,84.730700
XS GIS Cut Line= 4
844064.465385965  723179.5588508843786.867061233723025.189569092
843766.725268671722910.880518497843546.095155844722906.290667422
#Sta/Elev= 30
9625.72599.809329682.32498.596549728.092 95.31589737.98693.764519750.97790.04986
9842.51481.379529899.72579.545559922.60980.38258 9943.55 83.31279953.70482.80824
9974.01272.247699984.16672.02419 9994.3270.4962710014.6372.6193910024.7872.51473
10034.9471.4593910045.0977.1079110055.2478.8735310061.1578.5917910091.1679.50498
10101.1682.6039210111.1684.0624110151.1785.7618210211.1987.3388910221.1990.83695
10231.1999.7627410241.19104.4325 10261.2104.9208 10271.2109.772110280.11115.4542
#Mann= 3 , 0 , 0
9625.725    0.12       09625.725    0.12       010280.11    0.12       0
#XS Ineff= 2 , 0
       09949.568        10050.45       0
Bank Sta=9625.725,10280.11
Exp/Cntr=0.3,0.1

Type RM Length L Ch R = 3 ,10028.29,,,
BEGIN DESCRIPTION:
END DESCRIPTION:
Bridge Culvert--1,0,-1,-1, 0
Deck Dist Width WeirC Skew NumUp NumDn MinLoCord MaxHiCord MaxSubmerge Is_Ogee
28.865350,27.000000,2.6,0, 13, 13, , , 0.95, 0, 0,0,,
 9921.99 9924.97 9929.35 9935.02 9941.28 9965.32 9965.3210035.3210035.3210041.78
10045.6310055.6810055.72
   80.08   80.11   80.16   80.23   80.12   79.87   79.87   79.12   79.12   79.05
   78.88   78.30   78.30
 -919.92 -919.89 -919.84 -919.77 -919.88 -920.13   75.87   75.12 -920.88 -920.95
 -921.12 -921.70 -921.70
 9921.99 9924.97 9929.35 9935.02 9941.28 9949.45 9949.4510019.4510019.4510041.78
10045.6310055.6810055.72
   80.08   80.11   80.16   80.23   80.12   80.04   80.04   79.29   79.29   79.05
   78.88   78.30   78.30
 -919.92 -919.89 -919.84 -919.77 -919.88 -919.96   76.04   75.29 -920.71 -920.95
 -921.12 -921.70 -921.70
BR Coef=-1 , 0 , 0 ,, 0 ,,,0.8,0,1,0,
WSPro=,,,, 1 ,,,, 0 ,,,, 0 ,,,,-1 ,-1 ,-1 , 0 , 0 , 0 , 0 , 0
BC Design=,, 0 ,, 0 ,,,,,,

Type RM Length L Ch R = 1 ,9985.724,157.066600,157.066600,157.066600
XS GIS Cut Line= 5
844117.425015363723141.960484395843856.853033048723017.256815618
843828.349304503722847.371276078843692.280240332722841.717186542
 843531.74944099722842.557426435
#Sta/Elev= 30
9604.233 100.5329651.26699.570659684.52595.72774 9728.8793.424519762.12893.37163
9884.07688.305729895.397 87.33229915.67680.052569935.95679.926669946.09578.24949
9956.23573.651849964.74171.881379986.655  71.3159996.794 69.680710006.9369.99406
10027.2176.0719510065.3774.3124610078.7376.2532610098.7576.0931110108.7674.83503
10138.7875.5851810168.8179.8619810188.82 83.944610268.8486.6668110308.84 92.9815
10318.84100.673110338.84102.445410348.84108.730110358.84112.083610362.09111.9584
#Mann= 3 , 0 , 0
9604.233    0.12       09604.233    0.12       010362.09    0.12       0
#XS Ineff= 2 , 0
       09935.043        10031.75       0
Bank Sta=9604.233,10362.09
Exp/Cntr=0.3,0.1

Type RM Length L Ch R = 1 ,9828.657,247.227100,247.227100,247.227100
XS GIS Cut Line= 6
844173.860548712722860.374902434844077.689796544722836.063574106
843982.321291801722800.207829446843860.035451986722763.091502798
843691.820953455722714.317009871843568.345299742 722683.57588247
#Sta/Elev= 30
9739.97792.784099800.68990.304059831.63288.227779842.195 87.26979863.41384.33802
9895.46382.790959938.19777.97643 9948.7177.48777 9959.1677.629329969.61176.84302
9980.06171.154619990.51270.6750410000.96 67.060110021.8669.2485310032.3174.45487
10042.7677.3725210053.2177.2176510063.6776.3048110115.7475.6030210136.5774.44586
10219.8676.1148210251.0378.3600310271.64 82.503110292.25 83.429910312.8685.56773
10323.1687.4448910333.4790.7038710354.0891.1824910364.3891.9887610371.2493.00408
#Mann= 3 , 0 , 0
9739.977  0.0427       09739.977  0.0427       010371.24  0.0427       0
#XS Ineff= 2 , 0
       09950.814        10047.21       0
Bank Sta=9739.977,10371.24
Exp/Cntr=0.3,0.1

Type RM Length L Ch R = 1 , 9581.43,247.227100,247.227100,247.227100
XS GIS Cut Line= 6
844126.075561583722578.951697766843909.292341356722539.253568424
843907.345972126722538.793517503843843.342596588722527.648289208
843724.146669568722510.659805559843624.684965563722499.663308032
#Sta/Elev= 30
9778.61293.430399789.87292.649719800.03891.124559820.37189.738459850.86988.81284
9861.03687.877779871.20287.351149891.53587.625889901.701  84.2069911.86783.33009
9922.033 84.4313  9932.2 82.36849942.36678.222289962.69970.646919972.86567.68115
9983.03167.486459993.19766.1633810003.3865.7452710013.5371.2368510023.1174.37167
10033.8375.3427110065.9775.12446 10094.675.69387 10114.876.45807   1013577.57821
 10155.280.7666710205.6380.7809710245.8781.14443   1026682.8158810286.4385.33434
#Mann= 3 , 0 , 0
9778.612   0.055       09778.612   0.055       010286.43   0.055       0
#XS Ineff= 2 , 0
       0                10029.55       0
Bank Sta=9778.612,10286.43
Exp/Cntr=0.3,0.1

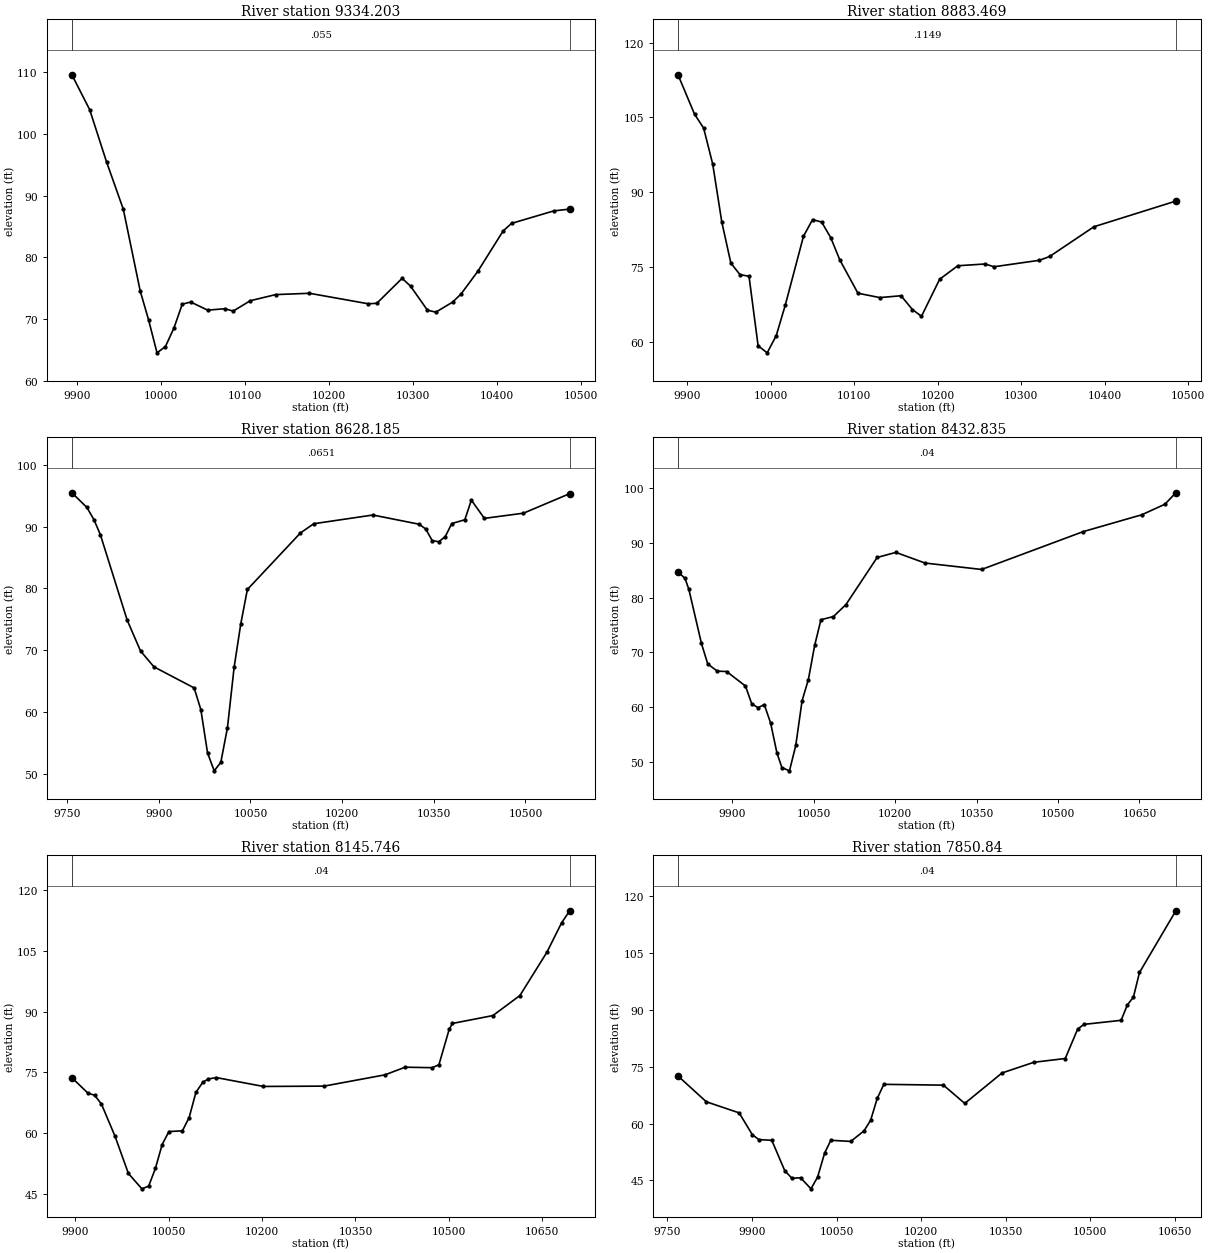
Type RM Length L Ch R = 1 ,9334.203,450.733800,450.733800,450.733800
XS GIS Cut Line= 6
844126.188282031722331.632270259843991.829258055722333.877594223
843866.982102255722316.664988599843818.357871515722314.564751947
843779.637170639722314.863819891843536.046750248722328.961582536
#Sta/Elev= 30
 9894.26109.57869915.448103.91719935.449 95.46419955.44987.765359975.46574.54693
9985.47369.832999995.48264.4938610005.4965.5166410015.4968.47341 10025.572.38042
10035.5372.7344410055.66  71.41910075.9471.6415410086.0971.2678310106.3772.94419
10136.6473.9380610176.7774.14972 10246.8 72.445310256.8272.5283710286.8676.57131
10296.8875.3133910316.9171.4245210326.92 71.086810346.9572.7177810356.96 74.0374
10376.9977.7319410407.0484.2640410417.0585.4858410467.1687.5057810486.1687.80188
#Mann= 3 , 0 , 0
 9894.26   0.055       0 9894.26   0.055       010486.16   0.055       0
#XS Ineff= 2 , 0
       0                10043.23       0
Bank Sta=9894.26,10486.16
Exp/Cntr=0.3,0.1

Type RM Length L Ch R = 1 ,8883.469,255.283600,255.283600,255.283600
XS GIS Cut Line= 2
843963.251471543721899.948080477 843414.73351305722134.448108073
#Sta/Elev= 30
9888.702113.55559908.551 105.6379919.427102.85789930.30295.627389941.178 84.0185
9952.05375.761389962.929 73.47349973.804 73.1218 9984.6859.190979995.55557.76776
10006.4361.2294110017.3167.3800410039.06 81.155410049.93 84.499110060.81 84.0055
10071.6880.8876710082.56  76.42510104.3169.72769 10130.568.8545110155.9469.22181
10169.5666.4609410180.4465.0967310202.1972.5278710223.9475.2383710256.57  75.594
10267.4475.0398110321.8276.3375110334.0177.0990310387.0783.0638810485.2488.21652
#Mann= 3 , 0 , 0
9888.702  0.1149       09888.702  0.1149       010485.24  0.1149       0
#XS Ineff= 2 , 0
       0                10039.27       0
Bank Sta=9888.702,10485.24
Exp/Cntr=0.3,0.1

Type RM Length L Ch R = 1 ,8628.185,195.349800,195.349800,195.349800
XS GIS Cut Line= 6
843987.484600675721610.194431549843783.715981295721701.669339368
 843612.89216431721773.964057321843463.765386996721833.588100253
843320.360338583721887.207521044843233.562327846721917.443010964
#Sta/Elev= 30
9757.89695.470139782.54293.088219794.047 91.10429804.46588.695719848.31174.86654
9870.23469.847369892.15667.280569957.92563.868079968.88660.365559979.84853.34481
9990.729   50.4410001.5951.8203910012.4557.4413210023.31 67.181410034.1774.20926
10045.0279.8088310131.8988.96883 10153.690.4566510250.3591.8684910326.0290.37838
10336.7189.6122810347.3987.7328210358.0687.5394610368.7488.3621410379.4190.48852
10400.7791.0997810411.4494.27654 10432.891.3257410496.7292.1660910572.3795.33152
#Mann= 3 , 0 , 0
9757.896  0.0651       09757.896  0.0651       010572.37  0.0651       0
#XS Ineff= 2 , 0
       0                               0
Bank Sta=9757.896,10572.37
Exp/Cntr=0.3,0.1

Type RM Length L Ch R = 1 ,8432.835,287.089800,287.089800,287.089800
XS GIS Cut Line= 6
843862.298783925721428.475639513843639.611823848721558.803050082
843427.160241413721676.759548849843248.260201159721762.632005443
  843149.4589938721804.230959869843046.168531845721843.389088624
#Sta/Elev= 30
9799.83484.67274 9812.7883.488959819.86381.479569843.01971.635449854.59767.89839
9872.30466.577999889.33166.518819924.06563.876839935.64360.646459947.22159.92018
9958.79960.485739970.39757.147419982.00551.715299991.15949.01207 10005.248.41421
10016.8153.0475210028.4161.1846310040.0165.0531210051.6171.2664110063.1675.95203
10086.1876.5364610109.1978.7106710166.7287.3014210201.1888.2266310254.8786.28728
10359.1485.1152110546.28 92.012810654.0995.0790510696.8797.0036810717.0199.09239
#Mann= 3 , 0 , 0
9799.834    0.04       09799.834    0.04       010717.01    0.04       0
#XS Ineff= 2 , 0
       0                               0
Bank Sta=9799.834,10717.01
Exp/Cntr=0.3,0.1

Type RM Length L Ch R = 1 ,8145.746,294.905700,294.905700,294.905700
XS GIS Cut Line= 2
843628.736398598721250.282599679 842891.22838095721560.009763648
#Sta/Elev= 30
9894.44873.664699920.19269.869569931.03869.326029941.88467.182079963.57759.29803
9985.269  50.02610006.9646.2308110017.8146.9023210028.6551.25405 10039.557.16481
10050.3460.3665210072.0460.5522310082.8863.8297810093.7370.0346910104.5872.49174
10113.2473.3315410126.2773.7060910202.19 71.5086 10299.871.5902810397.4274.37256
10429.9676.2614110473.3476.1403110484.1976.8617810500.6385.5760610505.8887.06332
10570.9689.0089310614.34 93.961410657.72104.648210681.41111.931610694.35114.8792
#Mann= 3 , 0 , 0
9894.448    0.04       09894.448    0.04       010694.35    0.04       0
#XS Ineff= 2 , 0
       0                               0
Bank Sta=9894.448,10694.35
Exp/Cntr=0.3,0.1

Type RM Length L Ch R = 1 , 7850.84,240.106200,240.106200,240.106200
XS GIS Cut Line= 6
843548.066035257720942.433760036843360.756677044721052.455490022
843119.680808465721201.075383029843044.868488506721242.965698684
842856.103899704 721333.45118112842775.211874417721366.119470536
#Sta/Elev= 30
9768.84572.583459819.02365.768739877.28162.835199900.58457.08903 9912.13 55.7819
9935.154 55.59069958.17847.560849971.03945.544449986.087 45.710810004.6642.77097
10016.4145.89496 10028.952.2480910039.8955.5929510075.1355.2994810098.6258.07425
10110.3660.8548410122.1166.6501710133.85 70.376210239.5670.1622310277.3365.33511
10343.4273.3780610399.8976.2015110455.52 77.197910477.5484.9619410488.5586.21273
10554.6287.28537 10565.691.3350810576.3993.4038810587.1799.9198510651.65116.2231
#Mann= 3 , 0 , 0
9768.845    0.04       09768.845    0.04       010651.65    0.04       0
#XS Ineff= 2 , 0
       09939.332                       0
Bank Sta=9768.845,10651.65
Exp/Cntr=0.3,0.1