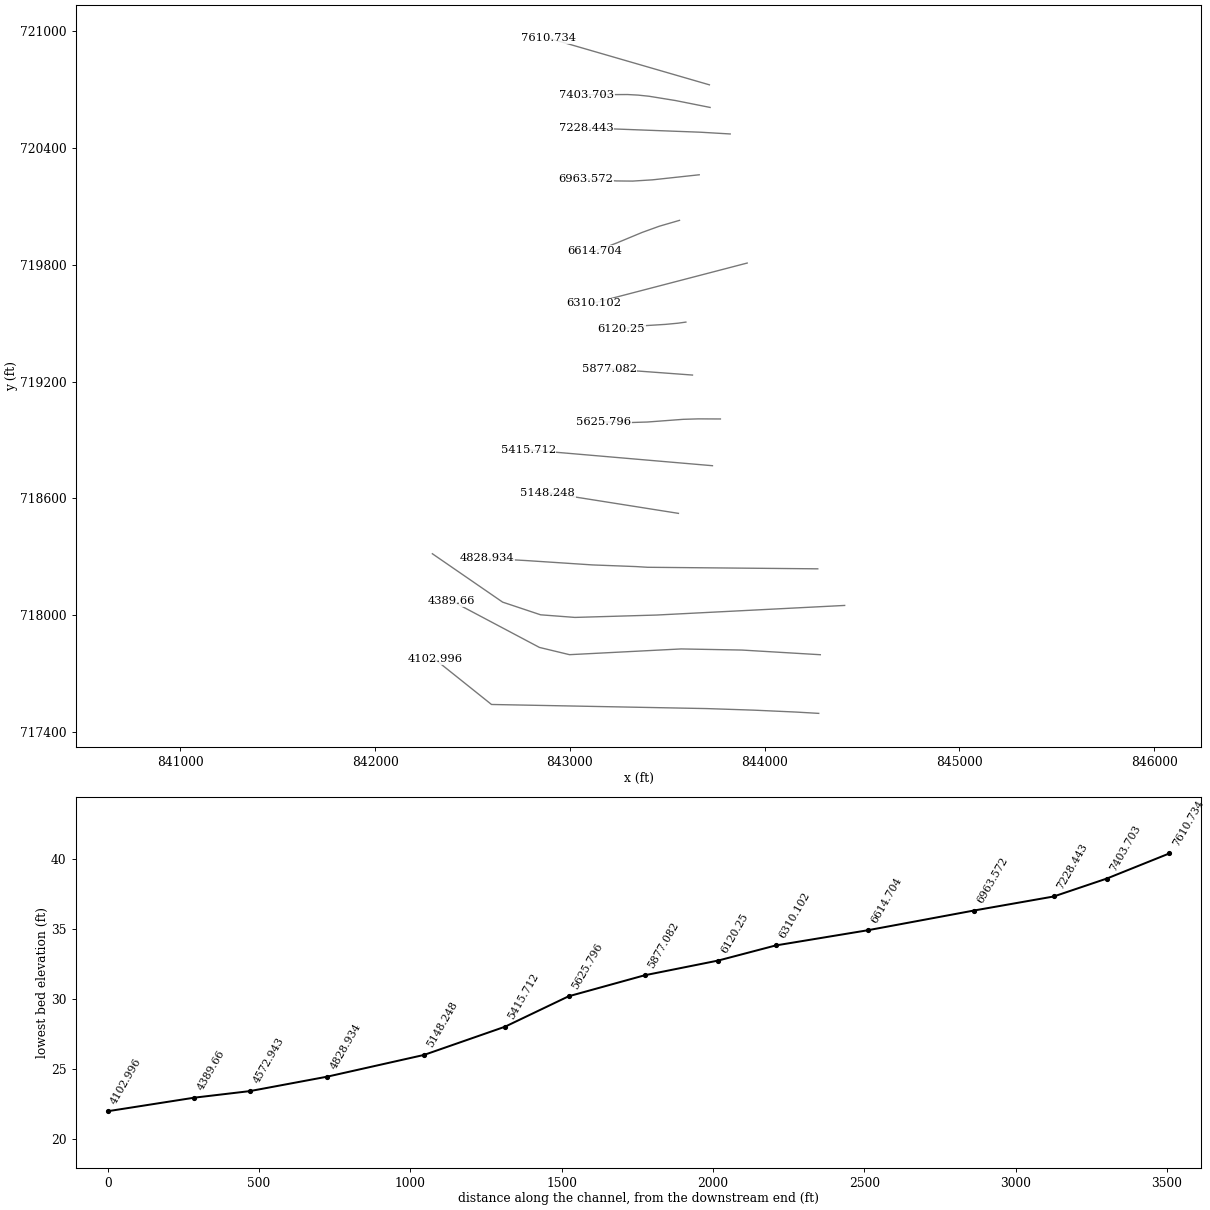
HEC-RAS study 7775_ras.prj: 7775

--- 7775_ras.g01 (geometry) --- (continued)

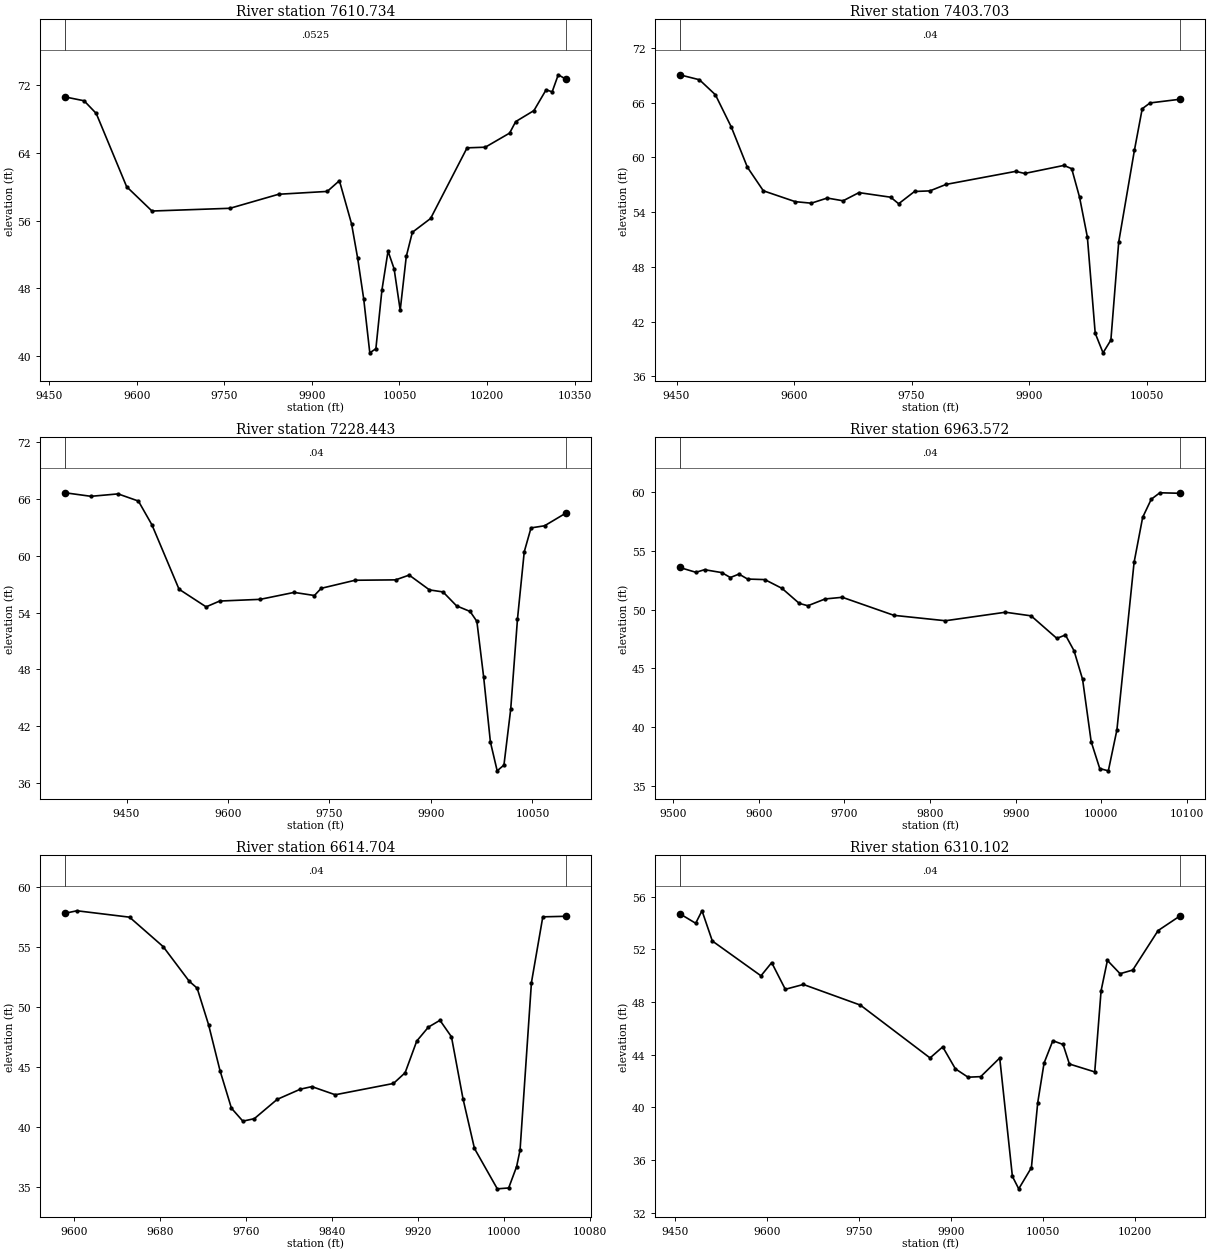
Type RM Length L Ch R = 1 ,7610.734,207.031000,207.031000,207.031000
XS GIS Cut Line= 2
843716.170499858720723.596796666842892.433561185720962.353542884
#Sta/Elev= 30
9477.38470.634829509.83770.182089530.66168.680999582.71960.022169626.10957.14428
9759.71557.468659843.00859.127359926.301 59.46329947.12460.731849967.94755.62596
9978.35951.57472 9988.77 46.73769999.18240.3753810009.5940.8604610020.0147.82768
10030.4252.4031710040.8350.3060110051.2445.4180610061.6551.7697210072.0654.62987
 10103.3 56.263410165.7764.61608   1019764.6932410238.6566.3598210249.0667.72023
10280.2969.0229410301.1271.4776510311.5371.2425510321.9473.2565310335.0272.73866
#Mann= 3 , 0 , 0
9477.384  0.0525       09477.384  0.0525       010335.02  0.0525       0
#XS Ineff= 2 , 0
       09946.543        10046.93       0
Bank Sta=9477.384,10335.02
Exp/Cntr=0.3,0.1

Type RM Length L Ch R = 1 ,7403.703,175.259500,175.259500,175.259500
XS GIS Cut Line= 6
843719.779468816720607.479832218843541.525894892720643.009727218
843405.751304196720664.992626889843350.021820542720670.792637771
843296.445788763720673.737263068 843086.29635523720672.838087502
#Sta/Elev= 30
9453.99369.05627 9479.2668.510819499.653 66.86399520.04663.31011 9540.4458.92789
9560.83356.33883 9601.6255.146859622.01454.980749642.36455.544319662.62455.24384
9682.88556.139389723.40555.635019733.53654.918519753.79656.263949773.36756.32885
9794.15957.041369882.983 58.47019894.42958.240159944.42959.120689954.429 58.7623
9964.42955.643169974.42951.263889984.42940.727479994.42938.5766410004.4339.97553
10014.4350.7229310034.4360.7603610044.4365.3333910054.4365.9696810093.1466.37869
#Mann= 3 , 0 , 0
9453.993    0.04       09453.993    0.04       010093.14    0.04       0
#XS Ineff= 2 , 0
       0                               0
Bank Sta=9453.993,10093.14
Exp/Cntr=0.3,0.1

Type RM Length L Ch R = 1 ,7228.443,264.870900,264.870900,264.870900
XS GIS Cut Line= 5
843823.102309801720471.262184832843669.863196457720480.267758302
843187.210878588720498.533057531843185.211838527720498.594895075
843083.496309503720502.291631281
#Sta/Elev= 30
9359.22366.663959397.391 66.2909 9437.4666.546359467.51165.790769487.54663.27615
  9527.6 56.47979567.62954.616069587.64355.228569647.68655.410099697.72256.14202
9727.74355.81462 9737.7556.572999787.786 57.42489847.82957.466169867.84357.97128
9897.86556.405889917.879 56.19219937.89354.720239957.90854.128679967.91553.08366
9977.92247.215089987.92940.339649997.936  37.29710007.9437.9081810017.9543.81496
10027.9653.3463310037.9660.4326210047.9762.9556210067.9863.1777710099.5164.51819
#Mann= 3 , 0 , 0
9359.223    0.04       09359.223    0.04       010099.51    0.04       0
#XS Ineff= 2 , 0
       0                               0
Bank Sta=9359.223,10099.51
Exp/Cntr=0.3,0.1

Type RM Length L Ch R = 1 ,6963.572,348.868000,348.868000,348.868000
XS GIS Cut Line= 6
843663.908075515720261.687093109843424.767008203720235.783175001
843321.638658792720229.260398418843239.242152896720229.986948471
843152.590161078720236.083998912843081.080028248720241.247307452
#Sta/Elev= 30
9507.49953.590279526.51853.177939536.57753.399759556.69453.153599566.75252.73565
9576.81153.025789586.86952.604089606.98652.558519627.10351.81025 9647.2250.53319
9657.279  50.3349677.39650.911049697.51351.052779757.82649.516269817.94649.05783
9888.01449.781379918.01549.474119948.05147.557459958.07647.84633  9968.146.51222
9978.12544.07121 9988.1538.769329998.17436.48249 10008.236.2884510018.22 39.7733
10038.2854.02743 10048.357.8555810058.3359.3944210068.3559.9437410092.3459.90094
#Mann= 3 , 0 , 0
9507.499    0.04       09507.499    0.04       010092.34    0.04       0
#XS Ineff= 2 , 0
       0 9965.77                       0
Bank Sta=9507.499,10092.34
Exp/Cntr=0.3,0.1

Type RM Length L Ch R = 1 ,6614.704,304.601900,304.601900,304.601900
XS GIS Cut Line= 6
843562.604087734720027.609470409843458.800178765719997.475895233
843370.305267006719965.489144249843241.442563537719911.884193236
843195.041259499719894.250200214843124.715356139719869.972076769
#Sta/Elev= 30
9591.96657.812949602.98658.017879651.87157.48601 9683.1755.035419707.35452.15966
9714.74551.582769725.37848.544819736.01144.728569746.64441.597089757.27740.51828
9767.91140.721849789.17742.328149810.74643.176429821.47943.390679843.23842.71312
9897.39143.653039908.22244.543979919.05347.182819929.88348.341449940.62948.90647
9951.32647.533859962.02442.399659972.72238.246719993.98334.8869110004.5534.96014
10011.94 36.738310015.1338.1087710025.7252.04298 10036.357.5139210057.7757.55946
#Mann= 3 , 0 , 0
9591.966    0.04       09591.966    0.04       010057.77    0.04       0
#XS Ineff= 2 , 0
       09937.013                       0
Bank Sta=9591.966,10057.77
Exp/Cntr=0.3,0.1

Type RM Length L Ch R = 1 ,6310.102,189.852300,189.852300,189.852300
XS GIS Cut Line= 2
843910.318390387719808.442906015843119.804724743719602.556568162
#Sta/Elev= 30
 9457.2954.718089483.45353.985739493.78654.935139510.62752.63853 9589.9849.99172
9607.45650.994139629.65648.966469659.12449.334269752.12647.765579865.79643.74865
9886.46344.59011 9907.1342.920589927.79842.284929948.46542.328279979.466 43.7437
10000.1334.7466810010.4733.7990710031.1335.4092510041.4740.35203 10051.843.36062
 10066.145.05872 10082.844.7734510093.1443.2873810134.4742.68747 10144.848.85277
10155.1451.16259 10175.8 50.151910196.4750.4302610237.81 53.430310274.1754.56178
#Mann= 3 , 0 , 0
 9457.29    0.04       0 9457.29    0.04       010274.17    0.04       0
#XS Ineff= 2 , 0
       09969.404                       0
Bank Sta=9457.29,10274.17
Exp/Cntr=0.3,0.1

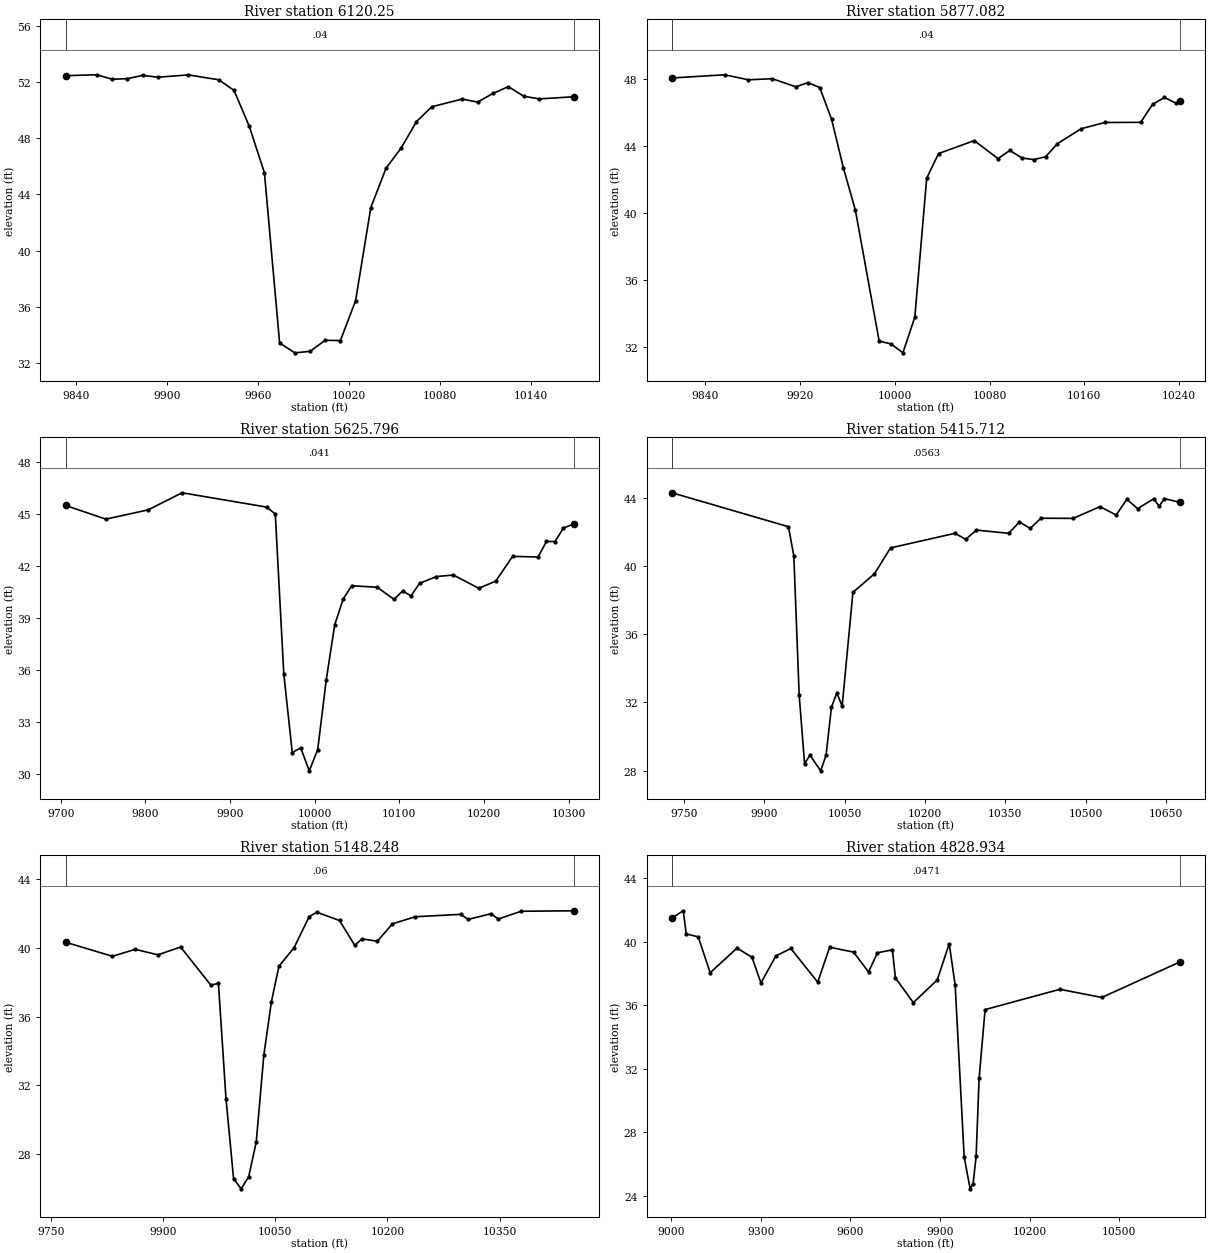
Type RM Length L Ch R = 1 , 6120.25,243.168200,243.168200,243.168200
XS GIS Cut Line= 6
843595.431438325719505.186103411843553.962842121719499.429903541
843489.281461785719493.329591877843379.425247536719486.563737129
843333.190202443719481.455224139843262.844446574719468.347423279
#Sta/Elev= 29
9833.13652.442869853.76352.506219863.85952.188199873.95552.230339884.00552.46439
9894.04952.332999914.13852.497599934.22752.14924 9944.2651.392939954.27848.84956
9964.29645.534199974.314  33.4269984.332 32.7207 9994.3532.8256410004.3733.61153
10014.3933.5941710024.4136.4265810034.4343.0461610044.45 45.847510054.49 47.3002
10064.5549.1726110074.6150.2294110094.7350.7789510104.8550.5612810114.99 51.1787
10125.1351.6640610135.2650.9809910145.4550.7905910168.1350.94012
#Mann= 3 , 0 , 0
9833.136    0.04       09833.136    0.04       010168.13    0.04       0
#XS Ineff= 2 , 0
       0                               0
Bank Sta=9833.136,10168.13
Exp/Cntr=0.3,0.1

Type RM Length L Ch R = 1 ,5877.082,251.286000,251.286000,251.286000
XS GIS Cut Line= 2
843629.312059597719233.183668785843201.862663944719264.757906965
#Sta/Elev= 30
 9812.1148.076699856.54348.267199876.59747.966949896.65248.033369916.70647.54635
9926.73347.800639936.76147.505949946.78845.609259956.81542.682699966.84240.18759
9986.89732.371029996.92432.2004810006.9531.6675210016.9833.7948710027.0142.09464
10037.0343.5656810067.1144.3362910087.1743.26365 10097.243.7515710107.2243.30438
10117.2543.2031110127.2843.3701810137.3144.1546910157.3645.0469710177.4145.42013
 10207.545.4265710217.5246.4942310227.55 46.913810237.58 46.559210240.7246.67355
#Mann= 3 , 0 , 0
 9812.11    0.04       0 9812.11    0.04       010240.72    0.04       0
#XS Ineff= 2 , 0
       0                               0
Bank Sta=9812.11,10240.72
Exp/Cntr=0.3,0.1

Type RM Length L Ch R = 1 ,5625.796,210.084500,210.084500,210.084500
XS GIS Cut Line= 6
843772.679418568719007.700290348843658.340654145719008.167807686
 843582.12298406 719005.90211421843398.823028559718992.111800393
843308.565202265718989.253621886843173.063493741718992.316314596
#Sta/Elev= 30
9705.555 45.51289753.24144.719499803.24145.257439843.25146.245079943.39545.41601
 9953.4245.013269963.44635.781429973.47131.223829983.49631.494759993.52230.16574
10003.5531.3901510013.5835.4080210023.6238.6109510033.6540.0976310043.6840.86958
10073.7740.78257 10093.840.0821910103.8140.5669110113.8140.2829910123.8241.00742
10143.8341.4009110163.8441.4887510193.8440.7225510213.8441.1353310233.8442.56913
10263.8642.5304610273.8643.4321510283.8743.4225110293.8844.2058610305.82 44.4406
#Mann= 3 , 0 , 0
9705.555   0.041       09705.555   0.041       010305.82   0.041       0
#XS Ineff= 2 , 0
       0                   10035       0
Bank Sta=9705.555,10305.82
Exp/Cntr=0.3,0.1

Type RM Length L Ch R = 1 ,5415.712,267.463900,267.463900,267.463900
XS GIS Cut Line= 2
843731.846091545 718767.67642971 842786.04833676718849.028449117
#Sta/Elev= 30
9727.29644.297799944.94342.30873 9954.9840.595279965.01732.424759975.05328.40884
 9985.0928.9099110005.1627.99195 10015.228.9045910025.2431.7149410035.2832.56378
10045.3131.7875810065.3938.4565410105.5339.5449110135.6441.0643310256.0941.92164
10276.1641.5687710296.2442.1094410356.4641.9216510376.5342.58406 10396.642.20788
10416.6842.80549 10476.942.7961410527.0843.48621 10557.242.9917610577.2743.91386
10597.3443.3699410627.4543.9435910637.4943.5120610647.5343.9540110676.5943.73609
#Mann= 3 , 0 , 0
9727.296  0.0563       09727.296  0.0563       010676.59  0.0563       0
#XS Ineff= 2 , 0
       0                10054.34       0
Bank Sta=9727.296,10676.59
Exp/Cntr=0.3,0.1

Type RM Length L Ch R = 1 ,5148.248,319.314100,319.314100,319.314100
XS GIS Cut Line= 3
843557.080947806718522.969265856 842920.90463305718623.700607167
 842885.78961761718629.753651714
#Sta/Elev= 30
9769.32340.341419832.17839.518659862.55139.927439892.92539.604479923.29940.06103
9963.79737.839879973.92237.942239984.04631.228689994.17126.57814 10004.3 25.9765
10014.4226.6841910024.5428.7058110034.6733.7598310044.7936.8683410054.9238.94186
10075.1740.0250810095.4241.8335810105.5442.0855810135.9241.6057910156.1640.16863
10166.2940.5300610186.5440.3992210206.7941.4101510237.1641.8234110297.9141.96232
10308.0341.6675110338.4141.9976710348.5341.69336 10378.942.1421910449.0642.17086
#Mann= 3 , 0 , 0
9769.323    0.06       09769.323    0.06       010449.06    0.06       0
#XS Ineff= 2 , 0
       09904.948        10100.21       0
Bank Sta=9769.323,10449.06
Exp/Cntr=0.3,0.1

Type RM Length L Ch R = 1 ,4828.934,255.990700,255.990700,255.990700
XS GIS Cut Line= 6
844272.777696551718238.152738221843399.044217242718246.084164124
843337.470546245718249.756790771843116.831832908 718258.13370846
842772.236614457718280.785206534842573.715343426718291.635372982
#Sta/Elev= 30
9003.12641.500559040.90541.952579050.90640.494869090.90740.308939130.90938.04892
9220.91339.600379270.91539.023829300.91637.401699350.91839.10656 9400.9239.57546
9490.92437.453239530.92639.656239610.92939.347879660.93138.094619690.93239.30648
9740.93439.490959750.93537.726799810.93736.161559890.96537.593229931.03639.87749
9951.05837.252439981.07826.4392410001.0924.42581 10011.124.7601510021.1126.46951
10031.1131.3944410051.1335.7242810301.5137.0029310441.8236.4889310703.5338.72849
#Mann= 3 , 0 , 0
9003.126  0.0471       09003.126  0.0471       010703.53  0.0471       0
#XS Ineff= 2 , 0
       09924.204        10125.15       0
Bank Sta=9003.126,10703.53
Exp/Cntr=0.3,0.1

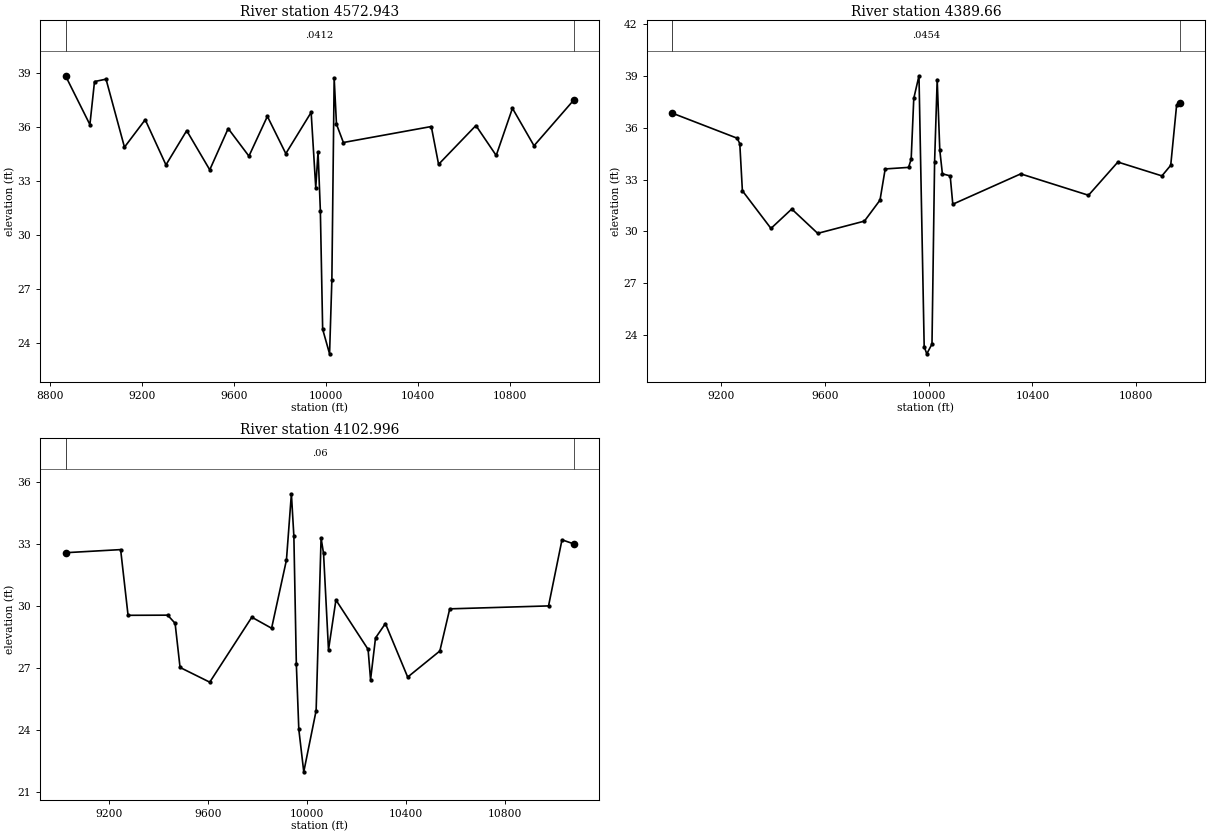
Type RM Length L Ch R = 1 ,4572.943,183.282400,183.282400,183.282400
XS GIS Cut Line= 6
844410.823512206718050.112067775843444.260205421718000.770124499
843025.539873788717988.596736924842849.432465977718002.008029695
842654.346798384718067.101668056842293.560271805718315.574418591
#Sta/Elev= 30
8868.92938.84019 8974.8936.127048994.916 38.51849044.98138.652829125.08534.87298
9215.20236.39972 9305.3233.888449395.43735.792969495.56733.615129575.67135.90984
9665.78834.376089745.89336.586659825.99734.517349936.05636.806479956.06532.63248
9966.06934.610599976.07431.351789986.07524.7605310016.0823.3919310026.0827.51365
10036.0838.7039410046.0836.15138 10076.135.1328410458.0536.0209510489.67 33.9203
10651.8836.0767610740.0334.4123610810.5537.0356210904.2834.9527811076.02 37.4778
#Mann= 3 , 0 , 0
8868.929  0.0412       08868.929  0.0412       011076.02  0.0412       0
#XS Ineff= 2 , 0
       09939.409        10042.96       0
Bank Sta=8868.929,11076.02
Exp/Cntr=0.3,0.1

Type RM Length L Ch R = 1 , 4389.66,286.664800,286.664800,286.664800
XS GIS Cut Line= 6
844285.785011792717797.049770593 843883.19187806717821.025608503
843571.492611702717826.765614037842997.908034372 717797.26756043
842843.317208038717834.542134111 842393.36915481718072.903833075
#Sta/Elev= 30
9011.26336.850679262.57735.39299 9272.5935.078819282.60332.354379392.74630.17615
9472.80131.298939572.84529.890769752.86530.599569812.88431.812059832.89333.61645
9923.00833.706369933.02934.184519943.05537.694289963.10739.003989983.15923.33376
9993.18522.9237410013.2323.4888810023.2534.0060910033.2838.78718 10043.334.70366
10053.3233.3336910083.3833.21577 10093.431.5758810355.2133.3310110616.3332.09407
 10729.534.0148810899.25  33.215 10933.2 33.826610955.8337.2953910968.9937.40747
#Mann= 3 , 0 , 0
9011.263  0.0454       09011.263  0.0454       010968.99  0.0454       0
#XS Ineff= 2 , 0
       09950.414        10041.02       0
Bank Sta=9011.263,10968.99
Exp/Cntr=0.3,0.1

Type RM Length L Ch R = 1 ,4102.996,124.255200,124.255200,124.255200
XS GIS Cut Line= 6
844277.549479919717495.841075235844159.484819325717502.650882833
843946.912327291717512.298862911843703.349640732717520.444549105
842597.198110106717541.551636428842306.016564139717774.164905488
#Sta/Elev= 30
9025.20932.569159248.06232.719479278.093 29.5365 9438.2229.543769468.23629.15016
9488.24827.010189608.31126.297469778.34229.444729858.35628.910469918.36732.21501
9938.37135.424119948.37233.376519958.37427.174839968.37624.010259988.376 21.9534
10038.3824.9219510058.3933.2785710068.3932.5310610088.3927.86217 10118.430.27972
10248.4327.8857310258.4326.4176910278.4328.4398610318.4429.1387110408.4626.54375
10538.4827.8076410578.4929.8494910977.9129.9919211032.2833.19472   1107932.99951
#Mann= 3 , 0 , 0
9025.209    0.06       09025.209    0.06       0   11079    0.06       0
#XS Ineff= 2 , 0
       09936.357        10065.27       0
Bank Sta=9025.209,11079
Exp/Cntr=0.3,0.1