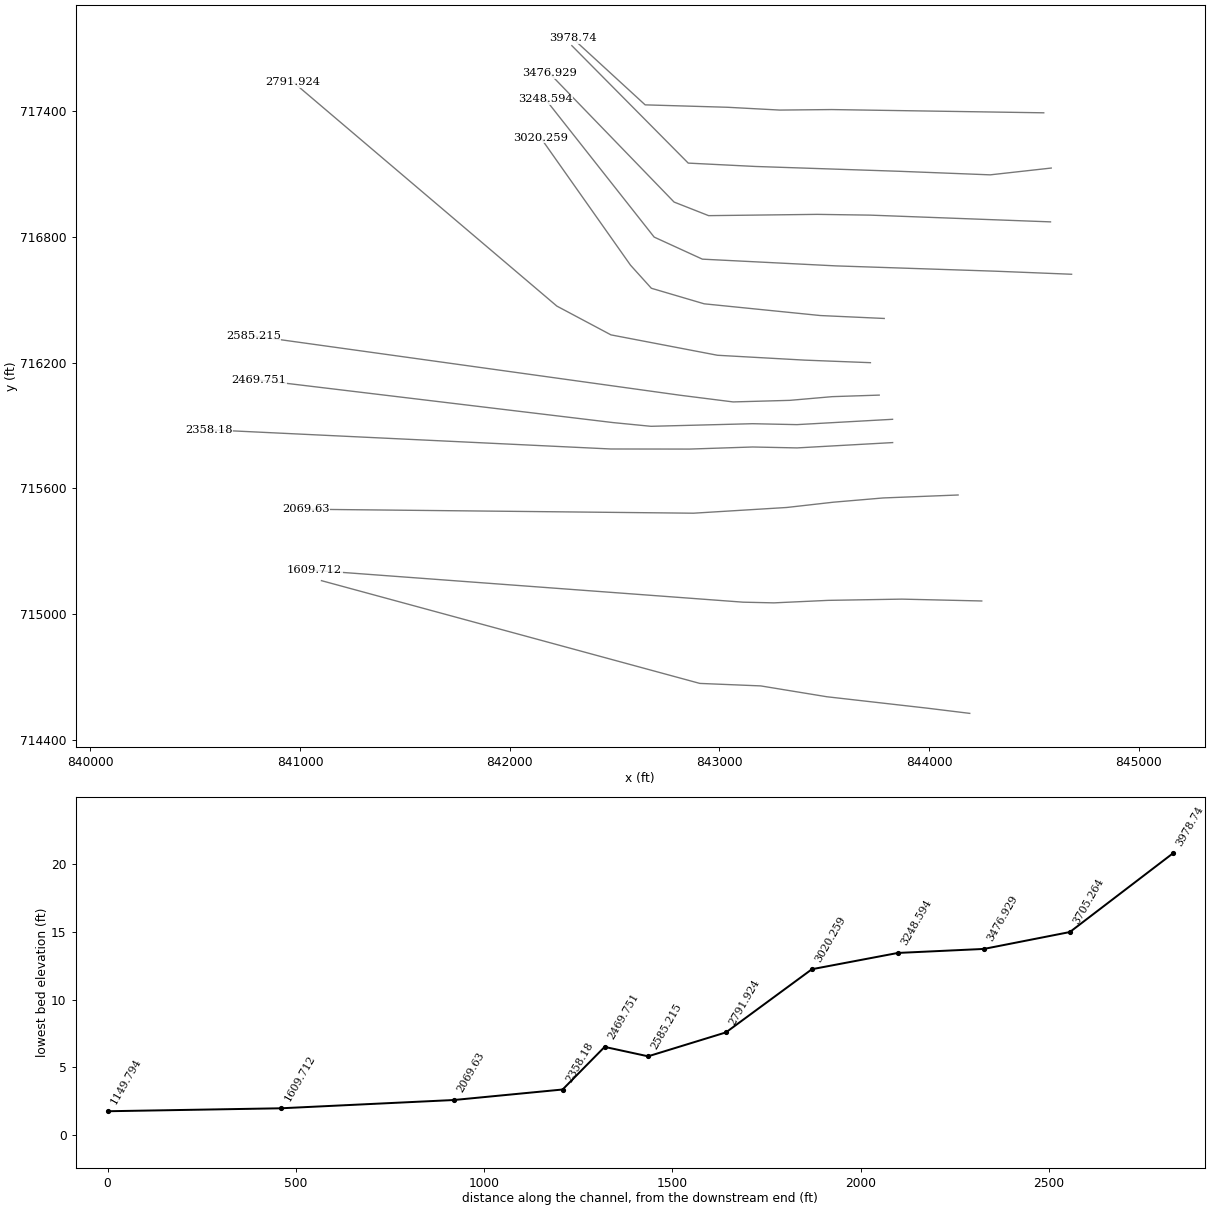
HEC-RAS study 7775_ras.prj: 7775

--- 7775_ras.g01 (geometry) --- (continued)

Type RM Length L Ch R = 3 ,4034.307,,,
BEGIN DESCRIPTION:
END DESCRIPTION:
Bridge Culvert--1,0,-1,-1, 0
Deck Dist Width WeirC Skew NumUp NumDn MinLoCord MaxHiCord MaxSubmerge Is_Ogee
39.127600,46.000000,2.6,0, 46, 46, , , 0.95, 0, 0,0,,
 9258.41 9285.04 9295.04 9325.04 9405.04 9455.04 9465.04 9505.04 9535.04 9545.04
 9565.04 9625.04 9655.04 9675.04 9695.04 9725.04 9745.04 9795.04 9825.04 9835.04
 9855.04 9865.04 9875.04 9895.04 9905.04 9915.04 9921.83 9952.92 9952.9210050.92
10050.9210077.1510085.0610105.0610125.0610165.0710225.0710255.0810275.0810315.08
10355.0910365.0910375.0910385.0910395.0910417.94
   29.40   29.33   29.18   29.15   28.84   28.37   28.37   27.97   27.83   27.90
   27.84   28.22   28.77   29.04   29.45   30.35   31.12   32.81   34.08   34.63
   35.52   35.87   36.34   37.02   37.19   37.53   37.64   37.57   37.57   37.34
   37.34   37.28   37.19   36.72   36.08   34.59   31.90   30.76   30.18   29.36
   28.98   29.04   28.63   27.55   27.36   27.58
 -970.60 -970.67 -970.82 -970.85 -971.16 -971.63 -971.63 -972.03 -972.17 -972.10
 -972.16 -971.78 -971.23 -970.96 -970.55 -969.65 -968.88 -967.19 -965.92 -965.37
 -964.48 -964.13 -963.66 -962.98 -962.81 -962.47 -962.36 -962.43   31.57   31.34
 -962.66 -962.72 -962.81 -963.28 -963.92 -965.41 -968.10 -969.24 -969.82 -970.64
 -971.02 -970.96 -971.37 -972.45 -972.64 -972.42
 9258.41 9285.04 9295.04 9325.04 9405.04 9455.04 9465.04 9505.04 9535.04 9545.04
 9565.04 9625.04 9655.04 9675.04 9695.04 9725.04 9745.04 9795.04 9825.04 9835.04
 9855.04 9865.04 9875.04 9895.04 9905.04 9915.04 9921.83 9946.80 9946.8010044.80
10044.8010077.1510095.0610105.0610125.0610165.0710225.0710255.0810275.0810315.08
10355.0910365.0910375.0910385.0910395.0910417.94
   29.40   29.33   29.18   29.15   28.84   28.37   28.37   27.97   27.83   27.90
   27.84   28.22   28.77   29.04   29.45   30.35   31.12   32.81   34.08   34.63
   35.52   35.87   36.34   37.02   37.19   37.53   37.64   37.58   37.58   37.35
   37.35   37.28   37.00   36.72   36.08   34.59   31.90   30.76   30.18   29.36
   28.98   29.04   28.63   27.55   27.36   27.58
 -970.60 -970.67 -970.82 -970.85 -971.16 -971.63 -971.63 -972.03 -972.17 -972.10
 -972.16 -971.78 -971.23 -970.96 -970.55 -969.65 -968.88 -967.19 -965.92 -965.37
 -964.48 -964.13 -963.66 -962.98 -962.81 -962.47 -962.36 -962.42   31.58   31.35
 -962.65 -962.72 -963.00 -963.28 -963.92 -965.41 -968.10 -969.24 -969.82 -970.64
 -971.02 -970.96 -971.37 -972.45 -972.64 -972.42
BR Coef=-1 , 0 , 0 ,, 0 ,,,0.8,0,1,0,
WSPro=,,,, 1 ,,,, 0 ,,,, 0 ,,,,-1 ,-1 ,-1 , 0 , 0 , 0 , 0 , 0
BC Design=,, 0 ,, 0 ,,,,,,

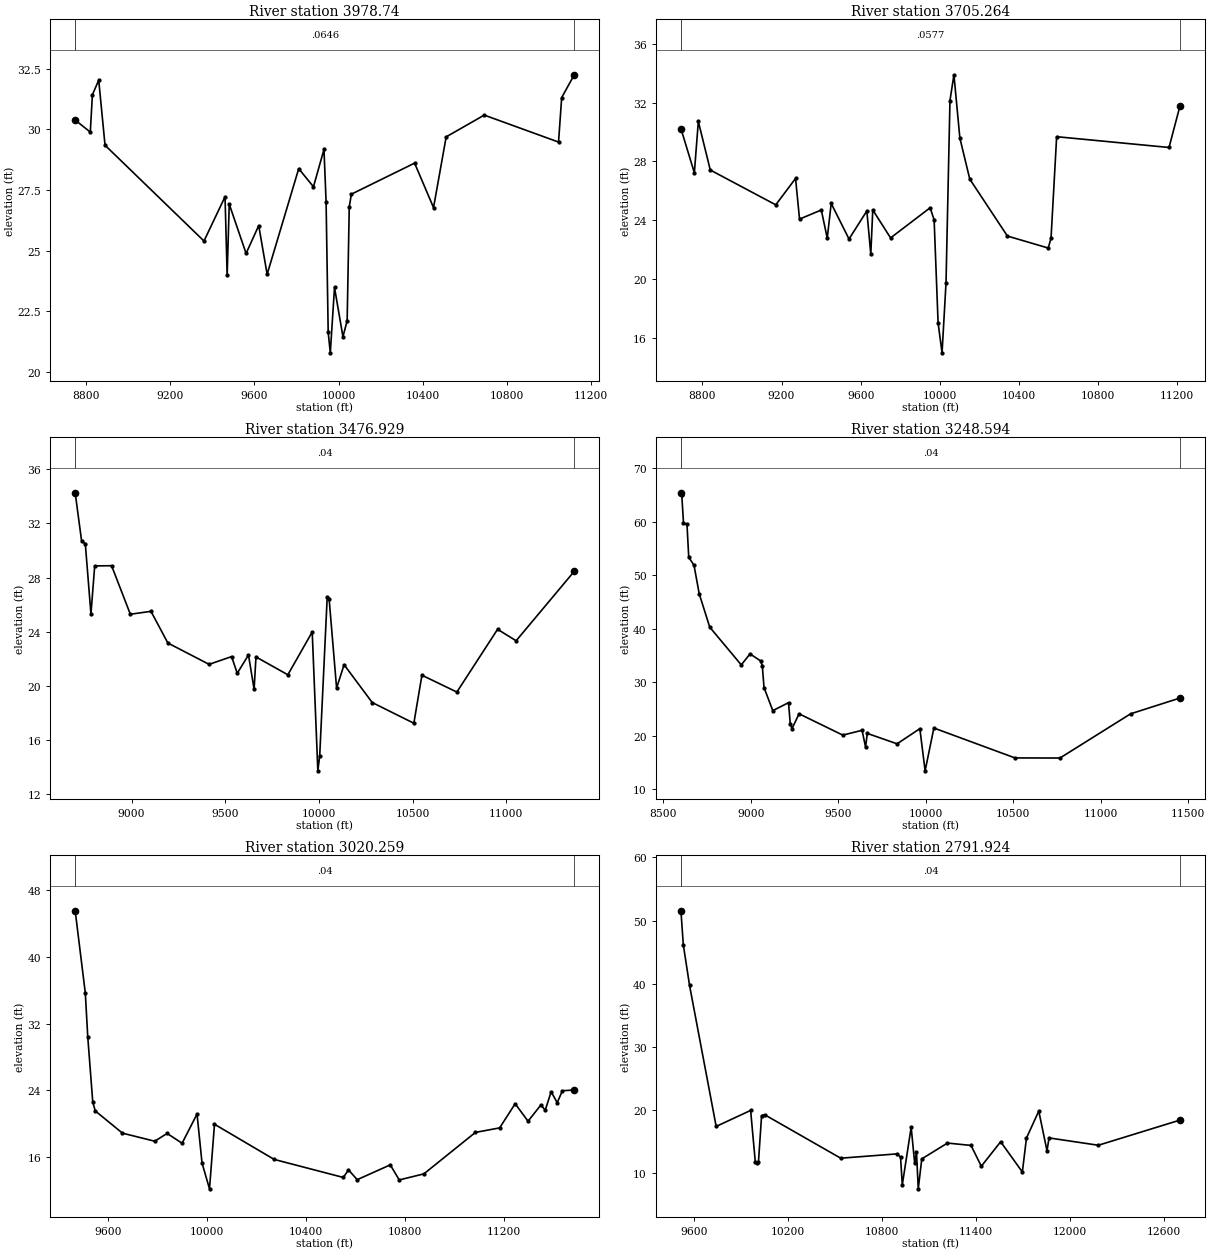
Type RM Length L Ch R = 1 , 3978.74,273.476800,273.476800,273.476800
XS GIS Cut Line= 6
844546.796713371717390.471760323843535.104749294 717405.95308979
843288.020265282717403.511040764843038.532422901717416.856960615
842645.619838364717428.359803426842299.906947065717745.418146943
#Sta/Elev= 30
8748.70630.387948820.51329.892128830.51431.432778860.51932.030718890.523 29.3503
9360.57925.40126 9460.5927.226369470.591 23.99589480.59226.92209  9560.6 24.8892
9620.607 26.03769660.61124.029549810.62428.383939880.62827.63841 9930.6329.17601
9940.63127.022429950.63121.639969960.63220.791529980.63323.4862710020.6621.45676
 10040.722.1139510050.7226.8128910060.7427.3324210361.0428.6124310451.0826.77923
10511.1129.6960610692.0930.5925611044.8829.4806511059.8431.3155111119.6432.25485
#Mann= 3 , 0 , 0
8748.706  0.0646       08748.706  0.0646       011119.64  0.0646       0
#XS Ineff= 2 , 0
       09913.297        10068.91       0
Bank Sta=8748.706,11119.64
Exp/Cntr=0.3,0.1

Type RM Length L Ch R = 1 ,3705.264,228.335000,228.335000,228.335000
XS GIS Cut Line= 6
844582.437845545717127.188966976844291.478209961 717094.80601131
843856.637322786717111.790962932843170.455130992717134.793842162
842851.049239945717150.759771639842295.879889505 717710.52127448
#Sta/Elev= 30
8691.61630.23362 8759.4727.231178779.59430.719458839.96427.417639170.99225.04933
9271.06926.846699291.08424.078549401.16824.699299431.18822.781829451.19925.14327
9541.24722.725489631.29524.631989651.30621.701159661.31124.69864 9751.3622.80029
9951.46724.852189971.47724.014579991.48817.01966 10011.514.9837310031.5219.74156
10051.5332.1444110071.5433.8949310101.57 29.588310151.6326.7985710341.86 22.9265
10548.1122.1120610562.3222.7739410590.72 29.683911158.7528.95017 11214.331.78784
#Mann= 3 , 0 , 0
8691.616  0.0577       08691.616  0.0577       0 11214.3  0.0577       0
#XS Ineff= 2 , 0
       09765.517         10062.7       0
Bank Sta=8691.616,11214.3
Exp/Cntr=0.3,0.1

Type RM Length L Ch R = 1 ,3476.929,228.335000,228.335000,228.335000
XS GIS Cut Line= 6
844579.031478052716870.662699392843719.163164361716902.805906011
843466.371098076716906.413060677842948.364087903716900.348515761
842783.571395936716965.103362807842189.236960044717578.986555229
#Sta/Elev= 30
8699.48434.253888733.54830.716748753.567 30.48188783.59625.313518803.61628.85858
8893.70328.872148993.79925.291549103.88825.506129193.93623.168529414.05221.59435
9534.11622.16616 9564.1320.932719624.136 22.28639654.13919.75525 9664.1422.14302
9834.15720.823489964.186 23.9816  9994.213.73644 10004.214.8566910044.2226.57711
10054.2226.4500110094.2319.8445810134.2521.5681210284.2518.7777610506.4117.24892
10549.5620.7927710735.9219.54876 10953.224.17971 11052.223.3341311362.3928.46111
#Mann= 3 , 0 , 0
8699.484    0.04       08699.484    0.04       011362.39    0.04       0
#XS Ineff= 2 , 0
       09826.698        10059.78       0
Bank Sta=8699.484,11362.39
Exp/Cntr=0.3,0.1

Type RM Length L Ch R = 1 ,3248.594,228.334900,228.334900,228.334900
XS GIS Cut Line= 6
844679.613940063716621.005532918844314.496240153716635.639949763
843554.914639077716660.924117434842918.523595215716692.976413585
842688.567259965716798.144887242842169.916453518717455.226105996
#Sta/Elev= 30
8600.94865.422458605.56665.084368615.57459.83336 8635.5959.515128645.59853.37353
8675.62251.879148705.64646.518068765.69440.296828945.83933.246688995.87235.30176
9055.90534.00861 9065.91 33.11449075.91629.013479125.94424.693659215.993  26.183
9225.99922.161499236.00521.334159276.02724.105229526.16520.117669636.22621.01715
9656.23717.893949666.24320.438419836.40818.489319966.56521.325949996.60113.44026
10046.6721.4452610510.3815.8536510767.44 15.834411170.9524.0979811453.5327.05282
#Mann= 3 , 0 , 0
8600.948    0.04       08600.948    0.04       011453.53    0.04       0
#XS Ineff= 2 , 0
       09955.854        10320.55       0
Bank Sta=8600.948,11453.53
Exp/Cntr=0.3,0.1

Type RM Length L Ch R = 1 ,3020.259,228.335000,228.335000,228.335000
XS GIS Cut Line= 6
843785.887402823716410.283901359 843481.37835612 716424.23965264
 842927.06878601716480.133061871842675.159262315716554.279236733
842575.928961513 716664.06820837842147.330778559717271.294090824
#Sta/Elev= 30
9468.83945.489499509.75535.646059519.76330.350169539.777  22.6479549.78421.56133
9659.863 18.89559790.12117.933419840.29418.865179900.63117.688069961.02721.18431
9981.15815.3293910011.3712.2385410031.5119.9627410272.7515.7540210551.95 13.5995
10572.7914.5062910607.9313.3329710741.4615.1052910777.7613.3024610877.2514.02897
11085.3318.9844511183.2519.5278111245.98 22.4158   1129820.3237911350.0222.27333
11367.3721.6385311391.33 23.851211415.8122.5385711436.7323.9684511484.7124.05777
#Mann= 3 , 0 , 0
9468.839    0.04       09468.839    0.04       011484.71    0.04       0
#XS Ineff= 2 , 0
       09964.824        10526.97       0
Bank Sta=9468.839,11484.71
Exp/Cntr=0.3,0.1

Type RM Length L Ch R = 1 ,2791.924,206.709200,206.709200,206.709200
XS GIS Cut Line= 6
843720.038655864716199.560654814843406.025918367716211.764549071
842990.582551889716234.898180302842482.562284765716332.087605034
842224.496853799716469.233997443840966.936830887717536.758506446
#Sta/Elev= 30
9515.46651.567629530.51646.224179570.54639.755519740.67517.446079960.90219.97911
9990.93811.7665410000.9511.7122710010.9611.8393610030.9919.1599210051.0319.29153
10536.5712.4211910896.1813.1009510918.8212.5863110930.158.21290910986.7717.30589
11009.4211.5960811020.74 13.385511032.07 7.5713711054.7212.3132711218.72 14.8142
11369.4414.4393711435.0311.1463911558.6715.0201511697.3710.23739 11723.615.60519
11802.3119.8741111854.7813.6000211867.8915.6282712182.7114.4675312704.8518.45093
#Mann= 3 , 0 , 0
9515.466    0.04       09515.466    0.04       012704.85    0.04       0
#XS Ineff= 2 , 0
       09956.857        10731.48       0
Bank Sta=9515.466,12704.85
Exp/Cntr=0.3,0.1

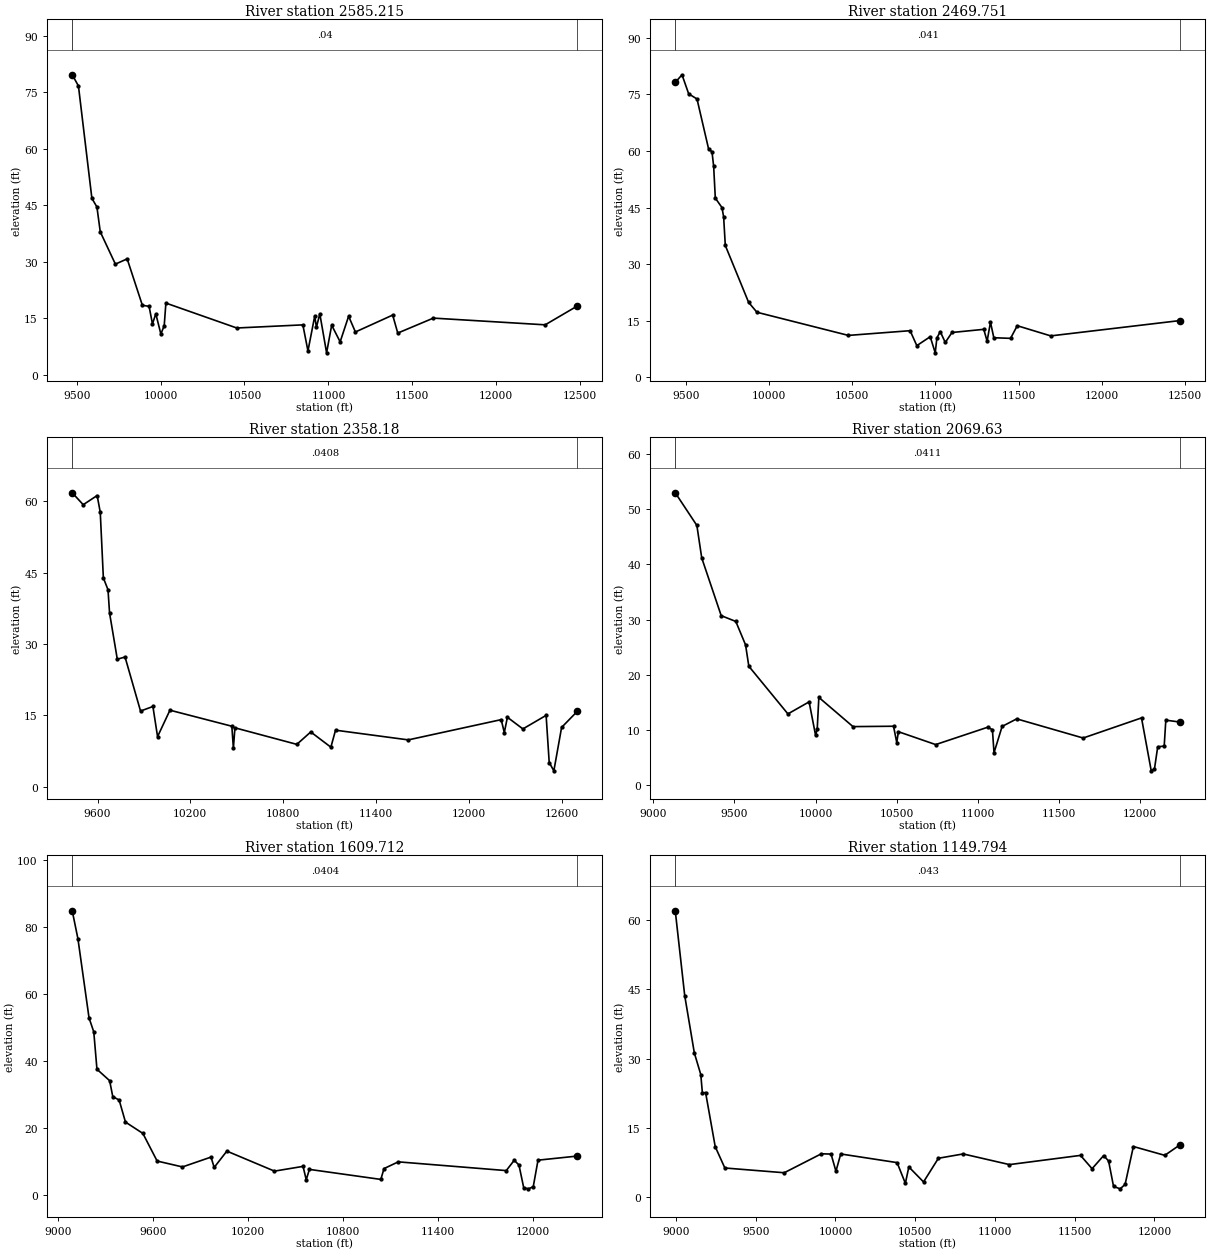
Type RM Length L Ch R = 1 ,2585.215,115.463200,115.463200,115.463200
XS GIS Cut Line= 6
 843762.01411505716045.022671668843538.075645568716037.658431947
843335.323202397716020.011176979 843065.21417698716012.508938628
842810.757767178716044.595896995840776.376135243 716327.11429181
#Sta/Elev= 30
9473.71279.593199510.74676.629279590.78946.812519620.80544.510969640.81637.91411
9730.911 29.34659801.04830.741539891.62318.426119931.70118.138619951.70913.47776
9971.71716.1716310001.7310.8125410021.74 12.978710031.7419.0119710454.0612.39881
10847.8613.2274810878.156.30815610918.5315.5617610928.6312.5889210948.8216.16961
 10989.25.80520611019.49 13.138511069.978.72256611120.4415.5204911160.8311.33824
11382.9315.8263711413.22 11.050611625.2215.0202112291.5313.2392212481.9618.20925
#Mann= 3 , 0 , 0
9473.712    0.04       09473.712    0.04       012481.96    0.04       0
#XS Ineff= 2 , 0
       09960.333        10896.02       0
Bank Sta=9473.712,12481.96
Exp/Cntr=0.3,0.1

Type RM Length L Ch R = 1 ,2469.751,111.570800,111.570800,111.570800
XS GIS Cut Line= 6
 843825.66523134715929.705920989843369.815021204715904.306192269
843158.002333945715908.709612553842673.344584094715896.300912634
842493.043675458715913.994693659840801.761125865716117.051690886
#Sta/Elev= 30
9434.60178.16573 9475.3380.187689515.392 75.13559565.46973.773199635.578 60.4664
9655.60959.801269665.62455.95836 9675.6447.503169715.70244.999539725.71842.51132
9735.73334.95602 9875.9519.881939925.97517.2544110476.2811.1200610847.7212.37077
10888.018.40860110968.5810.77453 10998.86.50099611008.8710.4509811029.0112.11694
11059.239.24885111099.5111.8920911290.8812.7293311311.029.58663811331.1714.63094
11351.3110.5035111452.0310.3390111492.3213.6886811693.7510.9911412472.5415.05847
#Mann= 3 , 0 , 0
9434.601   0.041       09434.601   0.041       012472.54   0.041       0
#XS Ineff= 2 , 0
       09962.561        10968.75       0
Bank Sta=9434.601,12472.54
Exp/Cntr=0.3,0.1

Type RM Length L Ch R = 1 , 2358.18,288.550700,288.550700,288.550700
XS GIS Cut Line= 6
843825.992497011715818.728041611843370.141534122715793.328271605
843158.328497075715797.731699003842857.563224791715787.808703084
842481.650829128715788.204353324840564.603431625715879.959827081
#Sta/Elev= 30
9436.45961.813929507.56259.305799597.70161.236129617.73257.710099637.76343.91752
 9667.8141.426989677.82636.538819727.90326.826519777.98127.283299878.13615.92085
9958.16216.882739988.19310.54487 10068.316.1031510468.4712.7327210478.478.113638
10488.4712.3998410888.628.91857110978.7211.5290211108.878.32499111138.9111.90003
11609.459.86078412210.1314.1186512230.1611.4035912250.1814.6181612350.2912.16542
12500.4615.0141912520.495.10556512550.523.35368712600.5812.4808212701.0915.83006
#Mann= 3 , 0 , 0
9436.459  0.0408       09436.459  0.0408       012701.09  0.0408       0
#XS Ineff= 2 , 0
       09956.689        10986.07       0
Bank Sta=9436.459,12701.09
Exp/Cntr=0.3,0.1

Type RM Length L Ch R = 1 , 2069.63,459.917700,459.917700,459.917700
XS GIS Cut Line= 6
844138.343239335715568.953607901843780.800916983715554.848387383
843543.603360728715534.645125189843320.949418404715509.433910216
842876.159286034715482.174025097 841026.45447351715501.108925462
#Sta/Elev= 30
9134.43652.975449267.83347.054519297.84541.164839417.97830.70445 9508.1329.65387
  9568.325.407019588.35721.537839829.58612.897089960.38415.0778610000.419.006845
10010.42   10.1310020.4315.89126 10231.110.5938910481.3310.6625710501.337.689142
10511.339.67106510741.387.336732 11061.410.47295 11091.410.04361 11101.45.856927
 11151.410.6314911241.41 11.995611651.43 8.5255112011.4512.1714312071.45 2.57794
12091.452.92997612111.466.93682212151.467.06241412161.46 11.762412250.0111.41538
#Mann= 3 , 0 , 0
9134.436  0.0411       09134.436  0.0411       012250.01  0.0411       0
#XS Ineff= 2 , 0
       09958.299        11032.33       0
Bank Sta=9134.436,12250.01
Exp/Cntr=0.3,0.1

Type RM Length L Ch R = 1 ,1609.712,459.917800,459.917800,459.917800
XS GIS Cut Line= 6
844251.089425322 715063.81040381843869.814383982715072.655163872
843518.344811284 715066.72372605843259.610674027715054.820004561
843113.347460625715058.084904268841068.593842152715209.827549967
#Sta/Elev= 30
9088.02884.948079124.13676.580659194.17252.988039224.18748.793899244.19737.65263
9324.22934.249569344.23129.462999384.23328.483769424.23621.89307 9534.2418.50204
9624.24210.261259784.2948.5030439964.475 11.43849984.4998.35461110064.5713.22455
10365.237.25227410545.778.66921810565.824.68257910585.867.76843311036.974.778409
11057.028.01196711147.2710.0201111829.117.40969511879.2510.4879211909.339.078513
11939.412.27626911969.491.96597811999.57 2.6102612029.6510.5228112276.7311.74025
#Mann= 3 , 0 , 0
9088.028  0.0404       09088.028  0.0404       012276.73  0.0404       0
#XS Ineff= 2 , 0
       09964.896        11076.78       0
Bank Sta=9088.028,12276.73
Exp/Cntr=0.3,0.1

Type RM Length L Ch R = 1 ,1149.794,0.000000,0.000000,0.000000
XS GIS Cut Line= 6
844193.877326031714528.119870906 843990.37656406714553.010835474
843511.982803005714607.380861832 843196.83502816714659.039501715
842906.293597412714670.929259528841101.771186644715160.672492093
#Sta/Elev= 30
  8995.162.040529054.41643.647869114.86331.206679155.16126.535499165.23622.55047
9185.38522.630199245.76710.884659306.1286.269618 9678.565.2373919911.4669.350784
9972.2289.28598110002.84 5.5668610032.869.31084110386.387.43404210438.192.940775
10460.046.49578210552.173.24533610645.428.37923910800.859.31691811090.987.003589
11536.53 9.0008511609.076.115987 11681.68.95784111712.687.79036411743.772.274451
11785.221.748584 11816.32.71197711868.1110.9288412064.989.01103812161.5811.31794
#Mann= 3 , 0 , 0
  8995.1   0.043       0  8995.1   0.043       012161.58   0.043       0
#XS Ineff= 2 , 0
       09712.145         10850.9       0
Bank Sta=8995.1,12161.58
Exp/Cntr=0.3,0.1